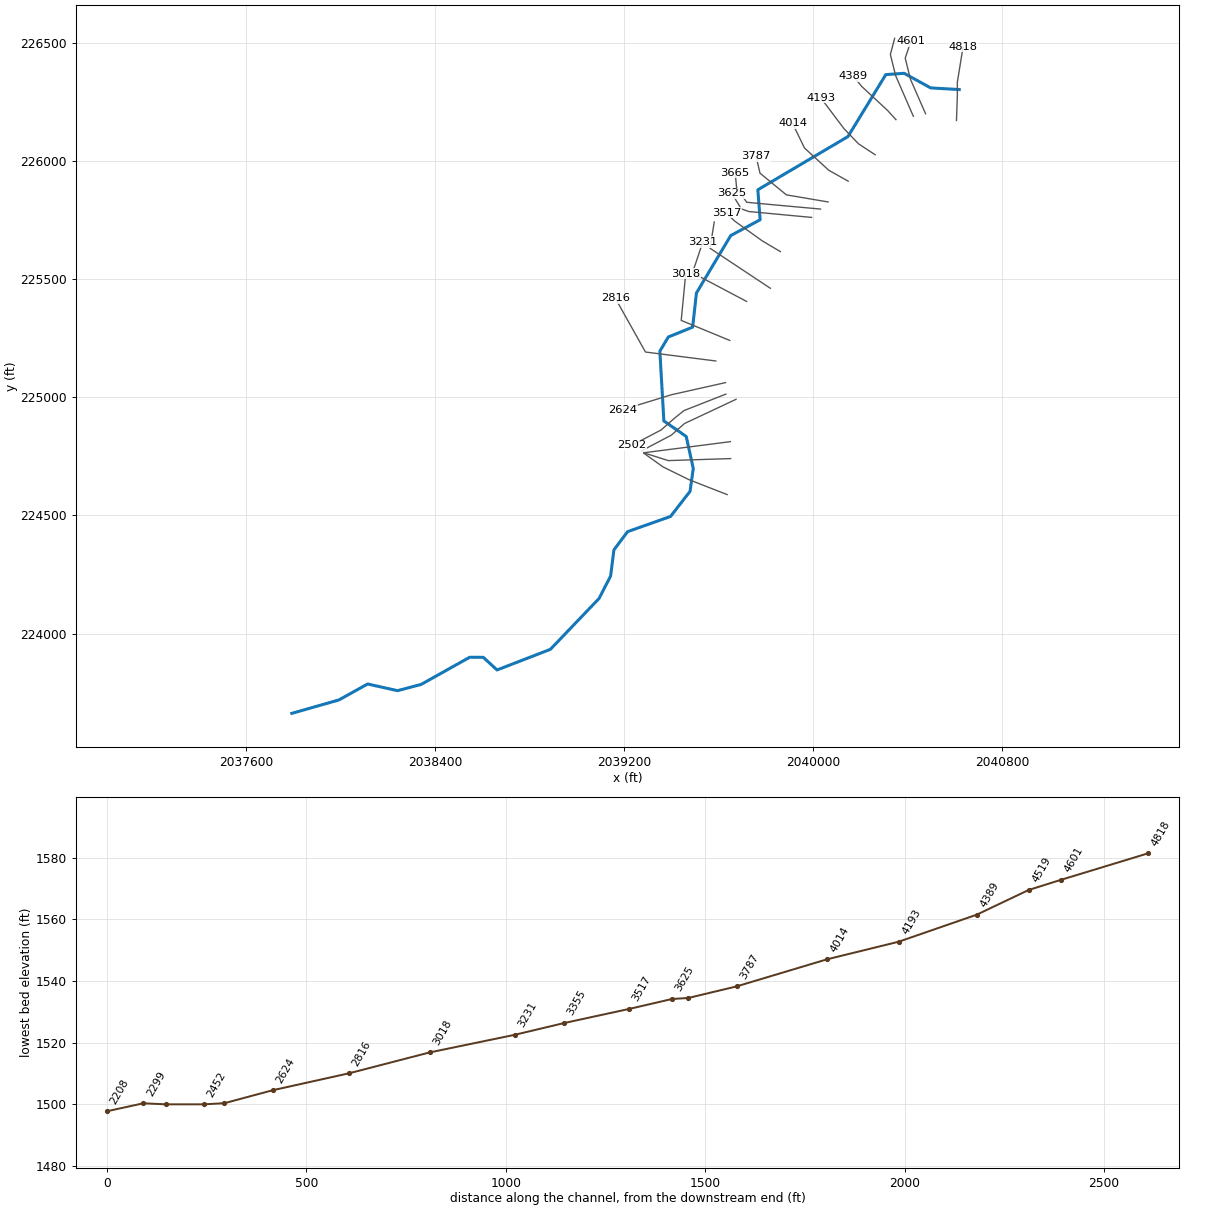
--- BLUELICK.prj (project) ---

Proj Title=BLUELICK
Current Plan=p01
Default Exp/Contr=0,0
English Units
Geom File=g01
Flow File=f01
Plan File=p01
BEGIN DESCRIPTION:
Stream Name: Blue Lick
Flood Zone: Detailed
Summers County, West Virginia
HEC-RAS Version: 5.0.7
Hydrology Method: Regression
Model Notes:
END DESCRIPTION:
DSS Export Rating Curves= 0
DSS Export Rating Curve Sorted= 0
DSS Export Volume Flow Curves= 0
DXF OffsetX= 0
DXF OffsetY= 0
DXF ScaleX= 0
DXF ScaleY= 0

--- BLUELICK.p01 (plan) ---

Plan Title=Floodplain
Program Version=5.07
Short Identifier=Floodplain
Geom File=g01
Flow File=f01
Subcritical Flow
K Sum by GR= 0
Std Step Tol= 0.01
Critical Tol= 0.01
Num of Std Step Trials= 20
Max Error Tol= 0.3
Flow Tol Ratio= 0.001
Split Flow NTrial= 30
Split Flow Tol= 0.02
Split Flow Ratio= 0.02
Log Output Level= 0
Friction Slope Method= 1
Unsteady Friction Slope Method= 2
Unsteady Bridges Friction Slope Method= 1
Parabolic Critical Depth
Global Vel Dist= 0 , 0 , 0
Global Log Level= 0
CheckData=True
Encroach Param=-1 ,5,5, 2
Encroach River=BLUELICK
Encroach Reach=Main
Encroach Node=4818
       1     116     165
Encroach Node=4601
       1     160     215
Encroach Node=4519
       1   185.1     230
Encroach Node=4389
       1     134     180
Encroach Node=4193
       1   117.6   148.5
Encroach Node=4014
       1     149   182.1
Encroach Node=3787
       1     257   291.6
Encroach Node=3665
       1   238.7     285
Encroach Node=3625
       1   199.4     258
Encroach Node=3517
       1   168.5   206.8
Encroach Node=3355
       1   235.8   273.7
Encroach Node=3231
       1     176   221.1
Encroach Node=3018
       1   149.7     193
Encroach Node=2816
       1     215   249.6
Encroach Node=2624
       1   263.1     297
Encroach Node=2502
       1     252   308.2
Encroach Node=2452
       1   269.1     315
Encroach Node=2356
       1   157.7     207
Encroach Node=2299
       1   147.5     184
Encroach Node=2208
       1   142.9   172.6
Encroach Node=2039
       1  294.35   322.8
Encroach Node=1992
       1   297.4   319.4
Encroach Node=1888
       1   312.9     337
Encroach Node=1743
       1   303.4   322.1
Encroach Node=1574
       1     170   202.6
Encroach Node=1386
       1      98     128
Encroach Node=1206
       1    67.3     102
Encroach Node=1065
       1      82   114.3
Encroach Node=860
       1     115     164
Encroach Node=792
       1     149     201
Encroach Node=734
       1     160   191.5
Encroach Node=632
       1   110.2   139.7
Encroach Node=505
       1   154.8     200
Encroach Node=380
       1  216.45     250
Encroach Node=227
       1     194   221.7
Encroach Node=150
       1   181.9     362
Mapping Interval=1HOUR
Computation Time Step Use Courant=        0
Computation Time Step Use Time Series=    0
Computation Time Step Count To Double=0
Computation Time Step Max Doubling=0
Computation Time Step Max Halving=0
Computation Time Step Residence Courant=0
Run HTab= 0
Run UNet= 0
Run Sediment= 0
Run PostProcess= 0
Run WQNet= 0
Run RASMapper= 0
UNET Theta= 0
UNET Theta Warmup= 0
UNET ZTol= 0
UNET ZSATol= 0
UNET MxIter= 0
UNET Max Iter WO Improvement= 0
UNET MaxInSteps= 0
UNET DtIC= 0
UNET DtMin= 0
UNET MaxCRTS= 0
UNET WFStab= 0
UNET SFStab= 0
UNET WFX= 1
UNET SFX= 1
UNET 1D Methodology=Finite Difference
UNET DSS MLevel= 1
UNET Pardiso=0
UNET DZMax Abort= 0
UNET Use Existing IB Tables= 0
UNET Froude Reduction=False
UNET Froude Limit= 0
UNET Froude Power= 0
UNET D1 Cores= 0
UNET D2 Coriolis=0
UNET D2 Cores= 0
UNET D2 Theta= 1
UNET D2 Theta Warmup= 1
UNET D2 Z Tol= 0.01
UNET D2 Volume Tol= 0.01
UNET D2 Max Iterations= 20
UNET D2 Equation= 0
UNET D2 RampUpFraction=0.1
UNET D2 TimeSlices= 1
UNET D2 BCVolumeCheck=0
UNET D1D2 MaxIter= 0
UNET D1D2 ZTol=0.01
UNET D1D2 QTol=0.1
UNET D1D2 MinQTol=1
Write IC File= 0
Write IC File at Fixed DateTime=0
Write IC File at Sim End=0
Echo Input=False
Echo Parameters=False
Echo Output=False
Write Detailed= 0
HDF Write Warmup=0
HDF Write Time Slices=0
HDF Flush=0
HDF Face Node Velocities=0
HDF Compression= 1
HDF Chunk Size= 1
HDF Spatial Parts= 1
HDF Use Max Rows=0
HDF Fixed Rows= 1
Calibration Method= 0
Calibration Iterations= 20
Calibration Max Change=0.05
Calibration Tolerance=0.2
Calibration Maximum=1.5
Calibration Minimum=0.5
Calibration Optimization Method= 1
WQ AD Non Conservative
WQ ULTIMATE=-1
WQ Max Comp Step=1HOUR
WQ Output Interval=15MIN
WQ Output Selected Increments= 0
WQ Output face flow=0
WQ Output face velocity=0
WQ Output face area=0
WQ Output face dispersion=0
WQ Output cell volume=0
WQ Output cell surface area=0
WQ Output cell continuity=0
WQ Output cumulative cell continuity=0
WQ Output face conc=0
WQ Output face dconc_dx=0
WQ Output face courant=0
WQ Output face peclet=0
WQ Output face adv mass=0
WQ Output face disp mass=0
WQ Output cell mass=0
WQ Output cell source sink temp=0
WQ Output nsm pathways=0
WQ Output nsm derived pathways=0
WQ Output MaxMinRange=-1
WQ Daily Max Min Mean=-1
WQ Daily Range=0
WQ Daily Time=0
WQ Create Restart=0
WQ Fixed Restart=0
WQ System Summary=0
WQ Write To DSS=0
WQ Use Fixed Temperature=0
Sorting and Armoring Iterations= 10
XS Update Threshold= 0.02
Bed Roughness Predictor= 0
Hydraulics Update Threshold= 0.02
Energy Slope Method= 1
Volume Change Method= 1
Sediment Retention Method= 0
XS Weighting Method= 0
Number of US Weighted Cross Sections= 1
Number of DS Weighted Cross Sections= 1
Upstream XS Weight=0
Main XS Weight=1
Downstream XS Weight=0
Number of DS XS's Weighted with US Boundary= 1
Upstream Boundary Weight= 1
Weight of XSs Associated with US Boundary= 0
Number of US XS's Weighted with DS Boundary= 1
Downstream Boundary Weight= 0.5
Weight of XSs Associated with DS Boundary= 0.5
Percentile Method= 0
Sediment Output Level= 3
Mass or Volume Output= 0
Output Increment Type= 1
Profile and TS Output Increment= 1
XS Output Flag= 0
XS Output Increment= 10
Write Gradation File= 0
Read Gradation Hotstart= 0
Write HDF5 File= 1
Write Binary Output= 1
Write DSS Sediment File= 0
SV Curve= 0
Specific Gage Flag= 0

--- BLUELICK.f01 (steady flow) ---

Flow Title=Flows
Program Version=5.07
Number of Profiles= 7
Profile Names=01pct,FW,10pct,04pct,02pct,0_2pct,01plus
River Rch & RM=BLUELICK,Main            ,4818
     493     493     259     346     417     691     730
River Rch & RM=BLUELICK,Main            ,2816
     637     637     338     449     540     888     942
River Rch & RM=BLUELICK,Main            ,1743
     711     711     379     502     603     989    1052
Boundary for River Rch & Prof#=BLUELICK,Main            , 1
Up Type= 0
Dn Type= 3
Dn Slope=0.026793
Boundary for River Rch & Prof#=BLUELICK,Main            , 2
Up Type= 0
Dn Type= 3
Dn Slope=0.026793
Boundary for River Rch & Prof#=BLUELICK,Main            , 3
Up Type= 0
Dn Type= 3
Dn Slope=0.026793
Boundary for River Rch & Prof#=BLUELICK,Main            , 4
Up Type= 0
Dn Type= 3
Dn Slope=0.026793
Boundary for River Rch & Prof#=BLUELICK,Main            , 5
Up Type= 0
Dn Type= 3
Dn Slope=0.026793
Boundary for River Rch & Prof#=BLUELICK,Main            , 6
Up Type= 0
Dn Type= 3
Dn Slope=0.026793
DSS Import GetInterval= 0
DSS Import GetPeak= 0
DSS Import FillOption= 0

--- BLUELICK.g01 (geometry) ---

Geom Title=Geometry
Program Version=5.07

River Reach=BLUELICK        ,Main
Reach XY= 30
     2040616.866      226302.628     2040496.032      226309.573
     2040383.594      226371.423      2040306.07      226365.779
     2040146.056      226103.5412039764.50815119225878.208441553
2039774.30300303225751.410083145      2039649.82      225684.529
     2039504.681      225441.474     2039488.537      225296.895
     2039385.516      225255.114     2039349.792      225195.138
     2039366.789      224899.679     2039461.355      224834.186
     2039491.284       224698.63     2039477.605      224601.904
     2039394.926      224495.502     2039213.155      224431.179
      2039155.43      224354.182     2039141.274      224243.311
     2039092.322      224148.193     2038886.482      223933.098
     2038660.681      223845.719     2038602.413      223899.169
     2038545.122      223899.603     2038339.452      223784.582
     2038239.566       223758.11      2038112.83      223786.322
     2037991.603       223718.94      2037791.83      223661.981

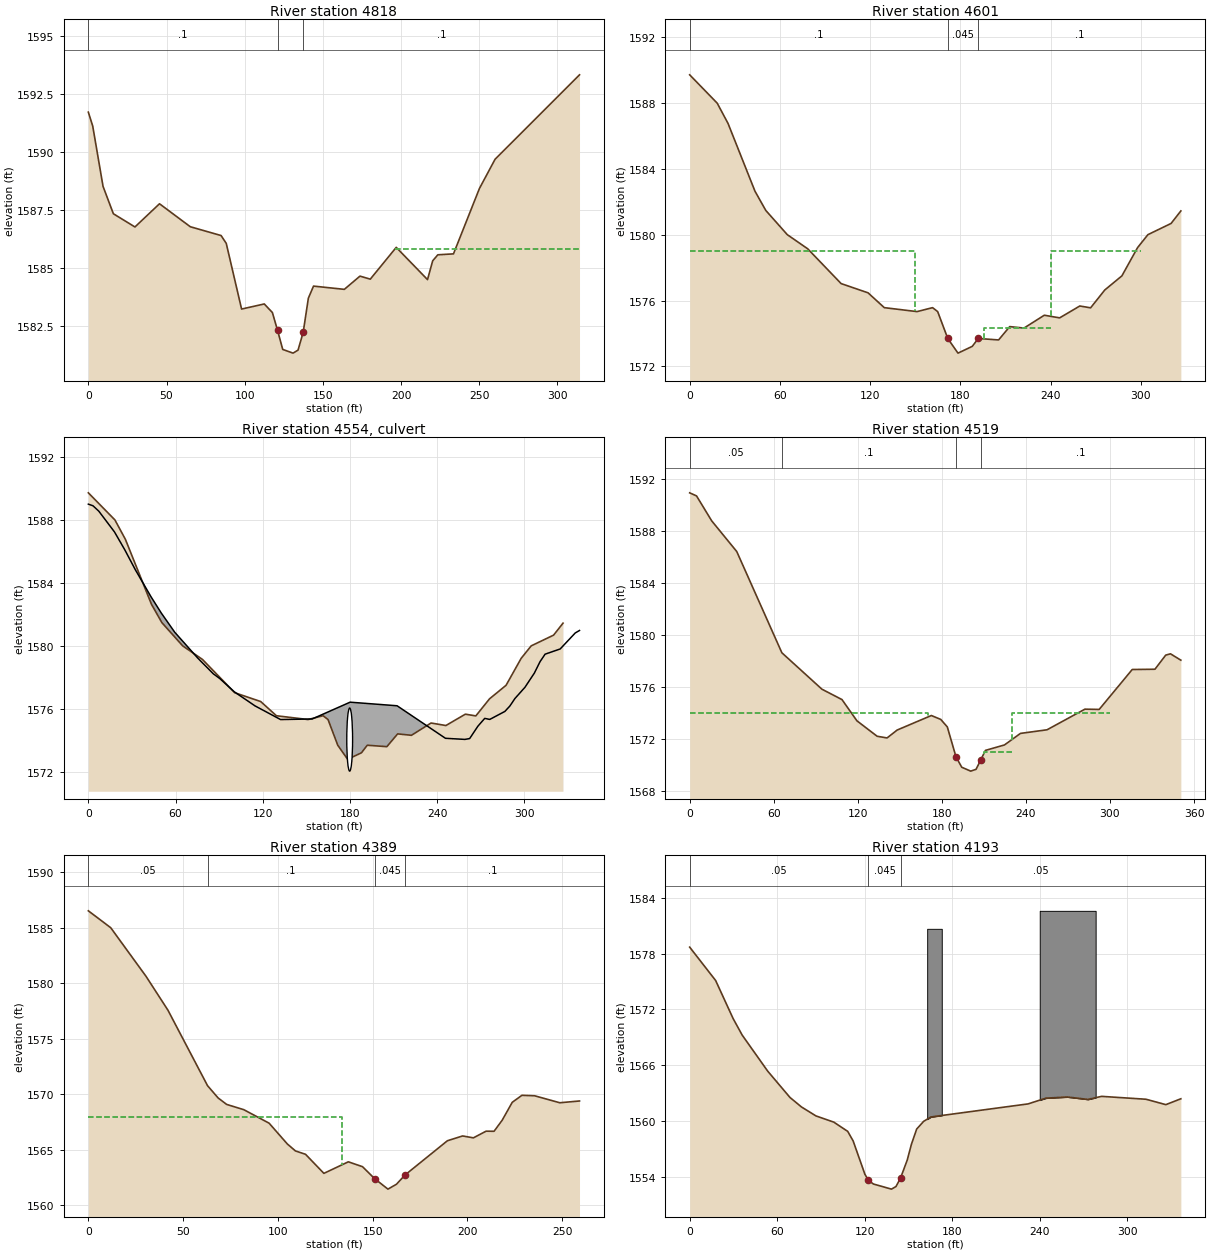
Type RM Length L Ch R = 1 ,4818    ,213.5,217,214.6
XS GIS Cut Line= 4
2040605.30863783226171.4939024212040609.06098477226276.774484962
2040609.06098477226333.7661258482040633.31572388226483.584227636
#Sta/Elev= 30
       0 1591.73     2.8 1591.13     9.4 1588.53      16 1587.35    29.8 1586.78
    45.5 1587.78    65.2 1586.79    84.9 1586.41    88.2 1586.07      98 1583.24
   112.5 1583.46   117.7 1583.09     121 1582.32   124.3  1581.5   130.9 1581.34
   134.1 1581.47   137.4 1582.24   140.7 1583.71     144 1584.23   163.7 1584.09
   173.7 1584.66   180.3 1584.53   196.9  1585.9   216.9 1584.51   220.2 1585.32
   223.5 1585.58   233.5 1585.62   250.1 1588.44   260.1  1589.7   314.1 1593.34
#Mann= 3 ,-1 , 0
       0      .1       0     121    .045       0   137.4      .1       0
#XS Ineff= 2 , 0
                             196         1585.84
Permanent Ineff=
       F       F
Bank Sta=121,137.4
XS Rating Curve= 0 ,0
Exp/Cntr(USF)=0,0
Exp/Cntr=0.5,0.3

Type RM Length L Ch R = 1 ,4601    ,82,81.6,77.5
XS GIS Cut Line= 4
2040474.55402816226200.2145681292040410.46632027226346.335649745
2040388.38825417226435.651462602 2040412.3039163226506.800097323
#Sta/Elev= 30
       0  1589.7    18.3 1587.98    25.5 1586.75    43.4 1582.64    50.6 1581.47
    64.9    1580    78.5 1579.14   100.7 1577.03   118.6 1576.47   129.4 1575.57
   151.2 1575.33   161.5 1575.57   164.9 1575.33   171.6  1573.7   178.4 1572.81
   187.9 1573.22   191.9  1573.7   205.4 1573.61   212.8 1574.42   222.3 1574.33
   235.8 1575.11     246 1574.95   259.4 1575.67   266.6 1575.56     276 1576.64
   287.4  1577.5   297.8 1579.21   304.7    1580   320.1 1580.68   326.6 1581.44
#Mann= 3 ,-1 , 0
       0      .1       0   171.6    .045       0   191.9      .1       0
#XS Ineff= 4 ,-1
       0     150    1579     150     162 1575.22     196     240 1574.31
     240     300    1579
Permanent Ineff=
       F       F       F       F
Bank Sta=171.6,191.9
XS Rating Curve= 0 ,0
Exp/Cntr(USF)=0,0
Exp/Cntr=0.5,0.3

Type RM Length L Ch R = 2 ,4554    ,,,
BEGIN DESCRIPTION:
Holly Lane
Survey ID: BLC050
END DESCRIPTION:
Bridge Culvert--1,0,-1,-1, 0
Deck Dist Width WeirC Skew NumUp NumDn MinLoCord MaxHiCord MaxSubmerge Is_Ogee
26,10,2.6,0, 34, 35, , , 0.98, 0, 0,0,,
       0   3.209   7.198  17.945   25.11  32.275  43.124  50.188  59.461  75.265
  86.013  90.369 100.343 114.673 132.282     154  180.09  212.42 245.705 259.081
 262.365 268.004 272.721 276.182 286.566 290.027 293.488 300.411 306.861 310.794
 314.256 324.639 335.023 337.935
1588.9821588.8781588.5371587.2261586.0821584.8331583.1111582.079 1580.861579.225
1578.2261577.9321577.0931576.1951575.3281575.3661576.4311576.2031574.1411574.071
1574.1251574.9061575.4041575.3371575.8441576.1881576.6621577.3761578.2741579.002
1579.4731579.804 1580.821580.975
                                                                                
                                                                                
                                                                                
                                
       0   3.209   7.198  17.945   25.11  32.275  43.124  50.188  59.461  75.265
  86.013  90.369 100.343 114.673 132.282     154  180.09  212.42 245.705 259.081
 262.365 268.004 272.721 276.182 286.566 290.027 293.488 300.411 306.861 310.794
 314.256 324.639 335.023 337.935     350
1588.9821588.8781588.5371587.2261586.0821584.8331583.1111582.079 1580.861579.225
1578.2261577.9321577.0931576.1951575.3281575.3661576.4311576.2031574.1411574.071
1574.1251574.9061575.4041575.3371575.8441576.1881576.6621577.3761578.2741579.002
1579.4731579.804 1580.821580.9751580.975
                                                                                
                                                                                
                                                                                
                                        
BR Coef=-1 , 1 , 0 ,, 0 ,,,0.8,0,1.2,0,
WSPro=,,,, 1 ,,,, 0 ,,,, 0 ,,,,-1 ,-1 ,-1 , 0 , 0 , 0 , 0 , 0
Culvert=1,4,,25,0.012,0.5,1,55,1,1572.06,179.8,1571.057,199,Culvert #1  , 0 ,13
   179.8     199
BC Culvert Barrel=1,Barrel1,0
Culvert Bottom n=0.012
BC Design=,, 0 ,, 0 ,,,,,,
BC Use User HTab Curves=0
BC User HTab FreeFlow(D)= 0

Type RM Length L Ch R = 1 ,4519    ,121,130.7,139.8
XS GIS Cut Line= 4
2040422.76024657226189.5092819772040347.64815064  226361.8332054
2040325.57008454226451.1490182572040343.63130866226519.378119277
#Sta/Elev= 30
       0 1590.97     4.9 1590.73    15.7 1588.81    33.6 1586.44    65.8 1578.63
    94.4 1575.82   108.7 1575.02   119.4 1573.38   133.8 1572.19   140.9 1572.06
   148.1 1572.67   172.5 1573.79   179.2 1573.49   183.9 1572.91   190.1  1570.6
   194.2  1569.8   200.6  1569.5   204.4 1569.64   207.8 1570.37   211.1  1571.1
   224.7 1571.52   236.1 1572.41   255.1 1572.69   282.1 1574.28   292.3 1574.26
   315.9 1577.34   332.1 1577.36   339.8 1578.45   343.2 1578.55   350.6 1578.06
#Mann= 4 ,-1 , 0
       0     .05       0    65.8      .1       0   190.1    .045       0
   207.8      .1       0
#XS Ineff= 4 ,-1
       0     170    1574     170     187    1571     210     230    1571
     230     300    1574
Permanent Ineff=
       F       F       F       F
Bank Sta=190.1,207.8
XS Rating Curve= 0 ,0
Exp/Cntr(USF)=0,0
Exp/Cntr=0.5,0.3

Type RM Length L Ch R = 1 ,4389    ,193.7,195.8,195.4
XS GIS Cut Line= 4
2040349.09006744226175.2729373822040314.19119062226213.588100502
2040205.03980884226315.0580002532040167.71536939226359.866928695
#Sta/Elev= 30
       0 1586.54    11.8 1585.02    30.4 1580.65      42 1577.59    62.9 1570.79
    68.5 1569.68      73  1569.1      82 1568.63    95.4 1567.41     105 1565.54
   109.3 1564.91   114.6 1564.61   124.3 1562.89   137.2 1563.93   144.7 1563.49
   151.1 1562.41   158.1 1561.47   162.6 1561.91   167.1 1562.74   189.5 1565.83
   197.5 1566.26   203.2 1566.09   209.9 1566.69   214.1 1566.68   218.4 1567.68
   223.7 1569.29   228.8 1569.92   235.5 1569.88   248.8 1569.25   259.2 1569.41
#Mann= 4 ,-1 , 0
       0     .05       0    62.9      .1       0   151.1    .045       0
   167.1      .1       0
#XS Ineff= 2 , 0
             134    1568
Permanent Ineff=
       F       F
Bank Sta=151.1,167.1
XS Rating Curve= 0 ,0
Exp/Cntr(USF)=0,0
Exp/Cntr=0.3,0.1

Type RM Length L Ch R = 1 ,4193    ,172.5,179.1,177.4
XS GIS Cut Line= 4
2040261.11483711226026.6423720132040191.25539497226072.430826837
2040129.30795923226136.8561600122040030.66659589226267.915377264
#Sta/Elev= 30
       0 1578.69    17.8 1575.11    29.8 1571.02      36 1569.25    53.5 1565.38
    68.8 1562.55    76.7 1561.53    86.6 1560.57    98.9  1559.9   108.4 1558.91
   112.1 1557.89   120.2  1554.3   122.6 1553.66     126 1553.26   138.4 1552.71
   141.5 1552.99   144.6 1553.89   149.2 1555.82   152.1 1557.53   155.7 1559.16
   160.5 1559.99   165.5 1560.46   232.1 1561.86   244.4 1562.48   259.1  1562.6
   273.2 1562.34   282.5 1562.67     313 1562.36   326.6 1561.78   336.9 1562.41
#Mann= 3 ,-1 , 0
       0     .05       0   122.6    .045       0   144.6     .05       0
#Block Obstruct= 2 ,-1
   162.9   172.9 1580.66   240.1  278.45 1582.59
Bank Sta=122.6,144.6
XS Rating Curve= 0 ,0
Exp/Cntr(USF)=0,0
Exp/Cntr=0.3,0.1

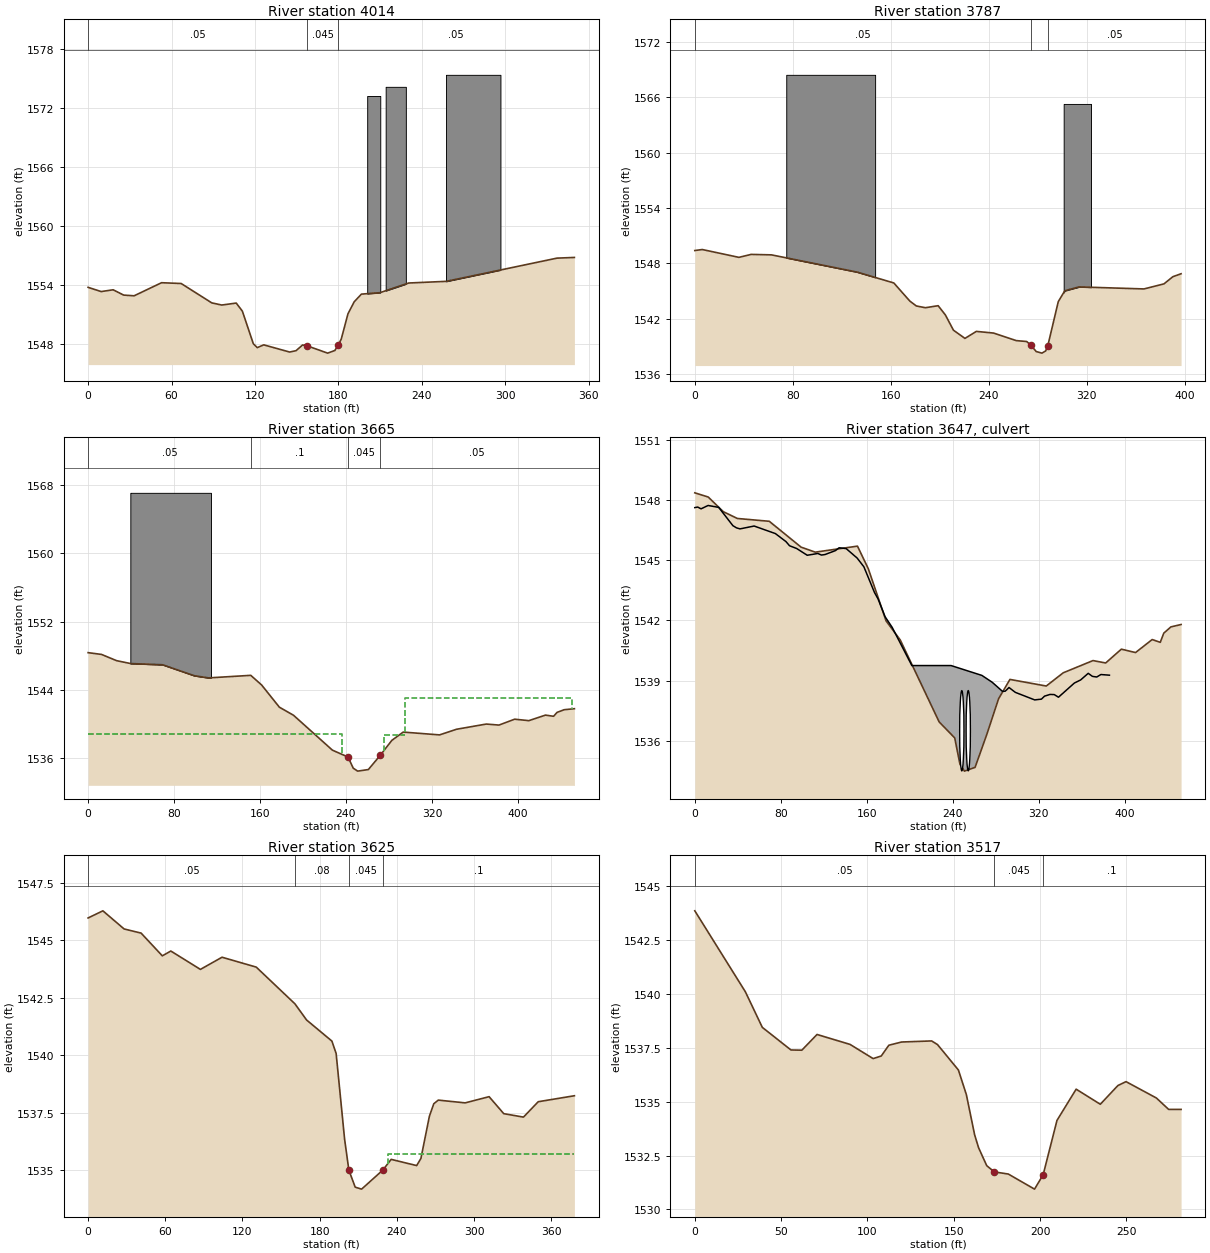
Type RM Length L Ch R = 1 ,4014    ,219.5,227.1,225.9
XS GIS Cut Line= 4
2040147.07890771 225914.754313582040064.88262605225960.925442496
2039962.04988272226055.0855448292039911.36042334 226159.31616892
#Sta/Elev= 30
       0 1553.72     9.4 1553.29      18 1553.47    25.6 1552.93    33.1 1552.86
    52.8 1554.19    66.9 1554.11    88.9 1552.14    96.1 1551.92   106.5 1552.12
   110.9  1551.3   118.8 1547.98   121.6 1547.59   126.3 1547.87   144.9 1547.14
   149.5 1547.28   154.2 1547.86   157.7 1547.76   172.2 1547.03   177.4  1547.3
   179.7 1547.83     182 1548.46   186.8 1551.02   191.3 1552.25   196.5 1553.03
   209.9 1553.18   230.5 1554.16   257.6 1554.33   337.1 1556.69   349.6 1556.76
#Mann= 3 , 0 , 0
       0     .05       0   157.7    .045       0   179.7     .05       0
#Block Obstruct= 3 ,-1
  200.64  210.04 1573.18  213.92  228.43 1574.11  257.32  296.44 1575.33
Bank Sta=157.7,179.7
XS Rating Curve= 0 ,0
Exp/Cntr(USF)=0,0
Exp/Cntr=0.3,0.1

Type RM Length L Ch R = 1 ,3787    ,85.5,121.3,125.6
XS GIS Cut Line= 4
2040061.88319403 225826.774586012039885.23506239225856.853750444
2039773.72967805225948.5359553472039756.87422556226020.125634283
#Sta/Elev= 30
       0 1549.38     6.1 1549.49      36 1548.64      46 1548.96    62.6 1548.91
   132.5 1547.04   162.5 1545.86   175.6 1543.89   180.9 1543.36   188.3 1543.17
   198.7 1543.39   204.6 1542.39   211.2 1540.73   220.6 1539.84   229.9  1540.6
   243.9 1540.42   262.5  1539.6     271  1539.5   274.2 1539.14   278.8 1538.41
   283.5 1538.24   286.5 1538.48   288.2 1539.01   296.8 1543.83   302.1 1545.01
   313.8 1545.43   366.8 1545.21   383.1 1545.76   390.4 1546.54   397.1 1546.86
#Mann= 3 ,-1 , 0
       0     .05       0   274.2    .045       0   288.2     .05       0
#Block Obstruct= 2 ,-1
   74.66  147.24 1568.46  301.22  323.55  1565.3
Bank Sta=274.2,288.2
XS Rating Curve= 0 ,0
Exp/Cntr(USF)=0,0
Exp/Cntr=0.5,0.3

Type RM Length L Ch R = 1 ,3665    ,38.8,40.4,38.5
BEGIN DESCRIPTION:
Channel burned from survey:54089BLC042CU
END DESCRIPTION:
XS GIS Cut Line= 5
2040029.76605198225796.7239211592039823.48328089 225815.45552227
2039717.10714422225825.4910068612039674.42801802225889.068669767
2039668.60923832225950.856584793
#Sta/Elev= 30
       0 1548.37    12.5 1548.16    26.5 1547.43    39.6 1547.09    69.3 1546.95
    98.9 1545.66   112.1 1545.41   151.4 1545.71   161.5 1544.58     178 1541.98
   191.2 1541.03   227.4 1536.94   241.9 1536.14  246.77 1534.83   250.91534.484
  260.85 1534.67   271.8 1536.32   282.7 1538.09   293.3 1539.06   327.1 1538.73
   342.9 1539.39   370.6    1540   382.4 1539.88     397 1540.57   410.2  1540.4
   425.7 1541.05   433.2 1540.91   436.5 1541.37   443.1 1541.68   452.6  1541.8
#Mann= 4 ,-1 , 0
       0     .05       0   151.4      .1       0   241.9    .045       0
   271.8     .05       0
#XS Ineff= 3 ,-1
       0     236 1538.81     275     295 1538.74     295     450    1543
Permanent Ineff=
       F       F       F
#Block Obstruct= 1 ,-1
    39.3  114.35  1567.1
Bank Sta=241.9,271.8
XS Rating Curve= 0 ,0
Exp/Cntr(USF)=0,0
Exp/Cntr=0.5,0.3

Type RM Length L Ch R = 2 ,3647    ,,,
BEGIN DESCRIPTION:
Phoenix Lane
Survey ID: BLC040
END DESCRIPTION:
Bridge Culvert--1,0,-1,-1, 0
Deck Dist Width WeirC Skew NumUp NumDn MinLoCord MaxHiCord MaxSubmerge Is_Ogee
15,10,2.6,0, 47, 23, , , 0.98, 0, 0,0,,
       0   2.673   5.783  12.372  22.256  35.435   38.73  42.024  55.203  74.971
  84.855   88.15  94.739 104.624 114.508 117.802 121.097 130.981 134.276 140.865
 151.036 157.339 167.223 170.517 177.107 183.693     202  238.49   267.2  276.81
  286.39  288.92 292.421 298.349 316.311 322.569 325.481 330.576 334.528 338.479
 353.209 359.095  366.14 370.091 374.043 377.994 385.897
1547.632 1547.661547.5711547.7391547.6431546.7321546.6231546.5711546.7131546.337
1545.9361545.7291545.5931545.2551545.3441545.2651545.289 1545.491545.6281545.588
1545.1171544.6811543.3971543.0791542.1881541.6571539.7521539.752 1539.261538.917
1538.4631538.4741538.6551538.4131538.0381538.0751538.225 1538.311538.3031538.172
1538.8781539.0341539.3631539.212 1539.181539.3041539.271
                                                                                
                                                                                
                                                                                
                                                                                
                                                        
 186.991  193.58     202  238.49   267.2  276.81  286.39  288.92 292.421 298.349
 316.311 322.569 325.481 330.576 334.528 338.479 353.209 359.095  366.14 370.091
 374.043 377.994 385.897
  1540.61540.6111539.7521539.752 1539.261538.9171538.4631538.4741538.6551538.413
1538.0381538.0751538.225 1538.311538.3031538.1721538.8781539.0341539.3631539.212
 1539.181539.3041539.271
                                                                                
                                                                                
                        
BR Coef=-1 , 1 , 0 ,, 0 ,,,0.8,0,1.2,0,
WSPro=,,,, 1 ,,,, 0 ,,,, 0 ,,,,-1 ,-1 ,-1 , 0 , 0 , 0 , 0 , 0
Culvert=1,4,,17,0.019,0.9,1,55,2,1534.498,248.5,1534.236,211,Culvert #1  , 0 ,11
   248.5     211
BC Culvert Barrel=1,Barrel1,0
Culvert Bottom n=0.019
Culvert=1,4,,17,0.019,0.9,1,55,2,1534.502,254.5,1534.023,217,Culvert #2  , 0 ,11
   254.5     217
BC Culvert Barrel=1,Barrel1,0
Culvert Bottom n=0.019
BC Design=,, 0 ,, 0 ,,,,,,
BC Use User HTab Curves=0
BC User HTab FreeFlow(D)= 0

Type RM Length L Ch R = 1 ,3625    ,105.6,107.6,78.1
BEGIN DESCRIPTION:
Channel burn based on survey: 54089BLC038CD
END DESCRIPTION:
XS GIS Cut Line= 5
 2039991.9379546225761.3645662172039832.51521702225776.317132367
2039726.13908036225786.3526169572039694.10045571225797.843082023
2039654.22300207225863.730164729
#Sta/Elev= 30
       0 1545.97    11.5 1546.28      28 1545.49    41.2 1545.31    57.7 1544.32
    64.3 1544.53    87.3 1543.73   104.1 1544.26   130.7 1543.83   160.8 1542.23
   169.8 1541.53   189.5 1540.61   192.8 1540.07   199.4 1536.33   202.7 1534.99
  207.63 1534.25   212.61534.165     229 1534.99   235.6 1535.46   255.4 1535.19
   258.7  1535.5   265.3 1537.34   268.7 1537.88   272.2 1538.04   293.1 1537.92
   311.7 1538.19   323.1 1537.45   338.4  1537.3   349.9 1537.97     378 1538.23
#Mann= 4 ,-1 , 0
       0     .05       0   160.8     .08       0   202.7    .045       0
     229      .1       0
#XS Ineff= 2 , 0
             196  1535.7     233          1535.7
Permanent Ineff=
       F       F
Bank Sta=202.7,229
XS Rating Curve= 0 ,0
Exp/Cntr(USF)=0,0
Exp/Cntr=0.5,0.3

Type RM Length L Ch R = 1 ,3517    ,153.9,162.9,155.7
XS GIS Cut Line= 5
2039859.91873794225616.6295854682039783.72266341 225661.70473997
2039666.71084033225745.6779306472039638.63874943225772.794761197
2039633.22371638225781.323765824
#Sta/Elev= 30
       0 1543.86    29.3  1540.1    39.1 1538.45    55.7  1537.4      62 1537.39
    70.8 1538.12    89.9 1537.66   103.3    1537     108 1537.12   112.4 1537.62
   119.8 1537.77   137.2 1537.82   140.6 1537.65   152.7 1536.47   157.3 1535.33
   162.1 1533.46   164.4 1532.86   169.1 1532.03   173.5 1531.74   181.6 1531.64
   196.8 1530.94   201.8 1531.61   209.8 1534.13   220.9 1535.58   234.9 1534.88
   245.1 1535.75   249.8 1535.93   267.4 1535.17   274.5 1534.64   281.7 1534.64
#Mann= 3 , 0 , 0
       0     .05       0   173.5    .045       0   201.8      .1       0
Bank Sta=173.5,201.8
XS Rating Curve= 0 ,0
Exp/Cntr(USF)=0,0
Exp/Cntr=0.3,0.1

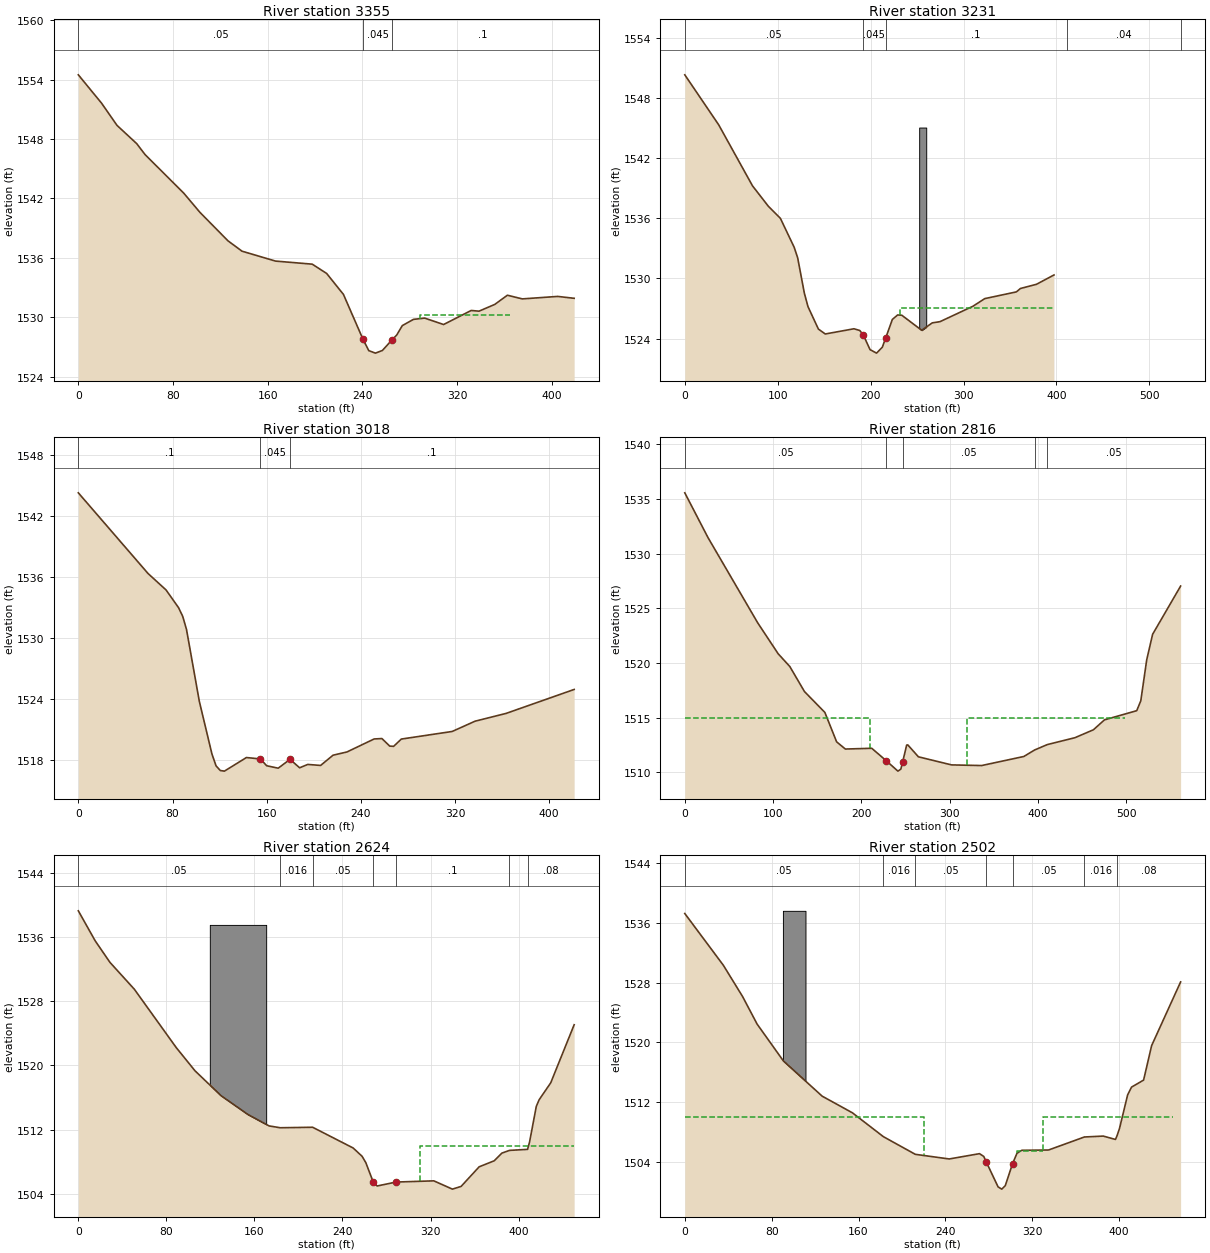
Type RM Length L Ch R = 1 ,3355    ,120.4,124.1,123.7
XS GIS Cut Line= 3
2039817.43630516225461.3736561982039562.08897501225630.861840397
2039580.00950236225741.872769577
#Sta/Elev= 30
       0 1554.49    19.6 1551.63    32.7 1549.38    49.3 1547.54    56.4 1546.43
    89.1 1542.53   102.7  1540.6   126.4 1537.72   138.3 1536.67   166.6 1535.67
   197.6 1535.36   209.8 1534.42     224  1532.3   240.5 1527.77   245.4 1526.62
     251 1526.37   256.9 1526.64   265.1 1527.72     269  1528.2   273.7 1529.15
   283.1 1529.78   292.6 1529.91   308.6 1529.26   331.9 1530.68   338.5 1530.61
   351.8 1531.29   362.5 1532.22   375.1 1531.85     405  1532.1   418.9 1531.91
#Mann= 3 ,-1 , 0
       0     .05       0   240.5    .045       0   265.1      .1       0
#XS Ineff= 1 ,-1
  288.45   364.8  1530.2
Permanent Ineff=
       F
Bank Sta=240.5,265.1
XS Rating Curve= 0 ,0
Exp/Cntr(USF)=0,0
Exp/Cntr=0.3,0.1

Type RM Length L Ch R = 1 ,3231    ,197.6,212.7,205.7
XS GIS Cut Line= 4
2039717.08145925225405.620964027 2039487.3803675225527.161832959
2039501.96713911225568.5764383042039531.53993788225657.408865788
#Sta/Elev= 30
       0 1550.32    36.5 1545.33    72.9 1539.24    89.9 1537.21   102.9    1536
   117.8  1533.1   121.5 1532.06   128.7 1528.53   132.6 1527.19   143.8 1524.95
   151.2 1524.46   182.1 1524.98   188.3 1524.81     192 1524.39   199.4  1522.9
   206.4 1522.55   212.6 1523.14   216.1 1524.02   223.4 1525.91   229.1 1526.36
   233.6 1526.33     255 1524.83   266.4 1525.57   274.7 1525.69   310.2 1527.23
   322.9 1527.99   356.9 1528.66   361.3    1529   378.6 1529.42   397.4 1530.35
#Mann= 5 ,-1 , 0
       0     .05       0     192    .045       0   216.1      .1       0
   411.2     .04       0   533.7    .016       0
#XS Ineff= 2 , 0
                          231.89         1527.08
Permanent Ineff=
       F       F
#Block Obstruct= 1 ,-1
  252.28  259.87 1545.06
Bank Sta=192,216.1
XS Rating Curve= 0 ,0
Exp/Cntr(USF)=0,0
Exp/Cntr=0.3,0.1

Type RM Length L Ch R = 1 ,3018    ,196.3,202.1,196.9
XS GIS Cut Line= 4
2039645.71801327225240.592995202 2039453.9287522225319.761818085
2039440.19244747225325.207090782 2039459.2156739225523.233304396
#Sta/Elev= 30
       0 1544.29    59.2 1536.34    74.5 1534.72    85.1 1532.98    88.7 1532.11
    91.9 1530.82   102.8 1523.73   113.5 1518.55     117 1517.38   120.6 1516.92
   124.1 1516.86   142.8  1518.2   154.7 1518.06     160 1517.39   169.8 1517.15
   179.8 1518.02     188 1517.19   194.9 1517.52   205.8 1517.42   216.4 1518.43
   228.2 1518.75   251.3 1520.03   257.9 1520.07   264.5 1519.33   267.8  1519.3
   274.4 1520.02   317.6 1520.77     337 1521.78   363.4 1522.55   421.2 1524.91
#Mann= 3 ,-1 , 0
       0      .1       0   154.7    .045       0   179.8      .1       0
Bank Sta=154.7,179.8
XS Rating Curve= 0 ,0
Exp/Cntr(USF)=0,0
Exp/Cntr=0.3,0.1

Type RM Length L Ch R = 1 ,2816    ,182.1,192,200.8
XS GIS Cut Line= 3
2039586.62015957225153.6187954162039288.90078338225191.530626092
2039161.16866593225419.420756809
#Sta/Elev= 30
       0 1535.56    26.3 1531.46    82.6 1523.66   105.7 1520.84   118.9 1519.67
   135.5 1517.38   158.6 1515.47   171.9 1512.78   181.8 1512.12   211.7 1512.19
   228.1 1511.05   241.3  1510.1   244.6 1510.28   246.7 1510.95   251.2 1512.48
   252.5  1512.5   264.5 1511.41     302 1510.67   336.1 1510.61   383.9 1511.44
     396 1512.03   410.5 1512.53   441.8 1513.16   462.6 1513.88   475.2 1514.79
   511.7 1515.63   516.3 1516.53     523 1520.28   529.7 1522.62   561.4 1527.03
#Mann= 5 ,-1 , 0
       0     .05       0   228.1    .045       0   246.7     .05       0
     396    .016       0   410.5     .05       0
#XS Ineff= 2 ,-1
       0  210.14    1515     320   498.6    1515
Permanent Ineff=
       F       F
Bank Sta=228.1,246.7
XS Rating Curve= 0 ,0
Exp/Cntr(USF)=0,0
Exp/Cntr=0.3,0.1

Type RM Length L Ch R = 1 ,2624    ,105,121.3,130
XS GIS Cut Line= 3
2039627.86860298225062.1245564952039398.45742524225010.642520544
2039192.52928144224947.418967623
#Sta/Elev= 30
       0 1539.23    15.3  1535.5    28.7 1532.82    50.9 1529.47      89  1522.2
     106 1519.32   129.6 1516.23   154.1 1513.88   173.3 1512.46   183.4 1512.23
   212.9 1512.29   249.7 1509.71   257.8 1508.68   261.2 1507.89   268.1 1505.42
   271.5 1504.98   288.7 1505.47     323 1505.62   339.9 1504.59   347.8 1504.93
   364.2 1507.37   377.9 1508.12   384.8 1509.07   391.7 1509.41   408.2 1509.54
     410 1510.47   416.1 1514.89   418.7 1515.72   429.2 1517.82   450.5 1525.05
#Mann= 7 ,-1 , 0
       0     .05       0   183.4    .016       0   212.9     .05       0
   268.1    .045       0   288.7      .1       0   391.7    .016       0
   408.2     .08       0
#XS Ineff= 2 , 0
                             310            1510
Permanent Ineff=
       F       F
#Block Obstruct= 1 ,-1
  119.46  170.67 1537.48
Bank Sta=268.1,288.7
XS Rating Curve= 0 ,0
Exp/Cntr(USF)=0,0
Exp/Cntr=0.5,0.3

Type RM Length L Ch R = 1 ,2502    ,45.4,50.3,42.4
BEGIN DESCRIPTION:
Channel burned based on survey : 54089BLC032CU
END DESCRIPTION:
XS GIS Cut Line= 5
2039629.04551777225013.3208626862039452.31760022224943.875753034
2039411.03264342224910.898706953 2039355.4320446224861.882389566
2039231.79387089224796.771161993
#Sta/Elev= 30
       0 1537.25    35.5 1530.33    53.2 1526.15    66.6 1522.46    90.8 1517.53
   126.5 1512.82   154.4 1510.59   182.9  1507.4   212.3 1505.04   243.5 1504.42
   271.4 1505.13   275.3 1504.76   277.81503.967  288.49 1500.69   291.91500.386
  295.12 1500.85   301.8 1503.78   305.9 1505.18   310.3 1505.58     335 1505.62
     368 1507.36   385.4 1507.48   396.6 1507.03   398.1 1507.55   400.3 1508.49
   407.8 1512.99   411.4 1514.03   422.5 1514.97   429.9 1519.58   456.6  1528.1
#Mann= 7 ,-1 , 0
       0     .05       0   182.9    .016       0   212.3     .05       0
   277.8    .045       0   301.8     .05       0     368    .016       0
   398.1     .08       0
#XS Ineff= 4 ,-1
       0     220    1510     220   271.8  1504.8   305.9     330 1505.54
     330     450    1510
Permanent Ineff=
       F       F       F       F
#Block Obstruct= 1 ,-1
   90.35  111.14 1537.61
Bank Sta=277.8,301.8
XS Rating Curve= 0 ,0
Exp/Cntr(USF)=0,0
Exp/Cntr=0.5,0.3

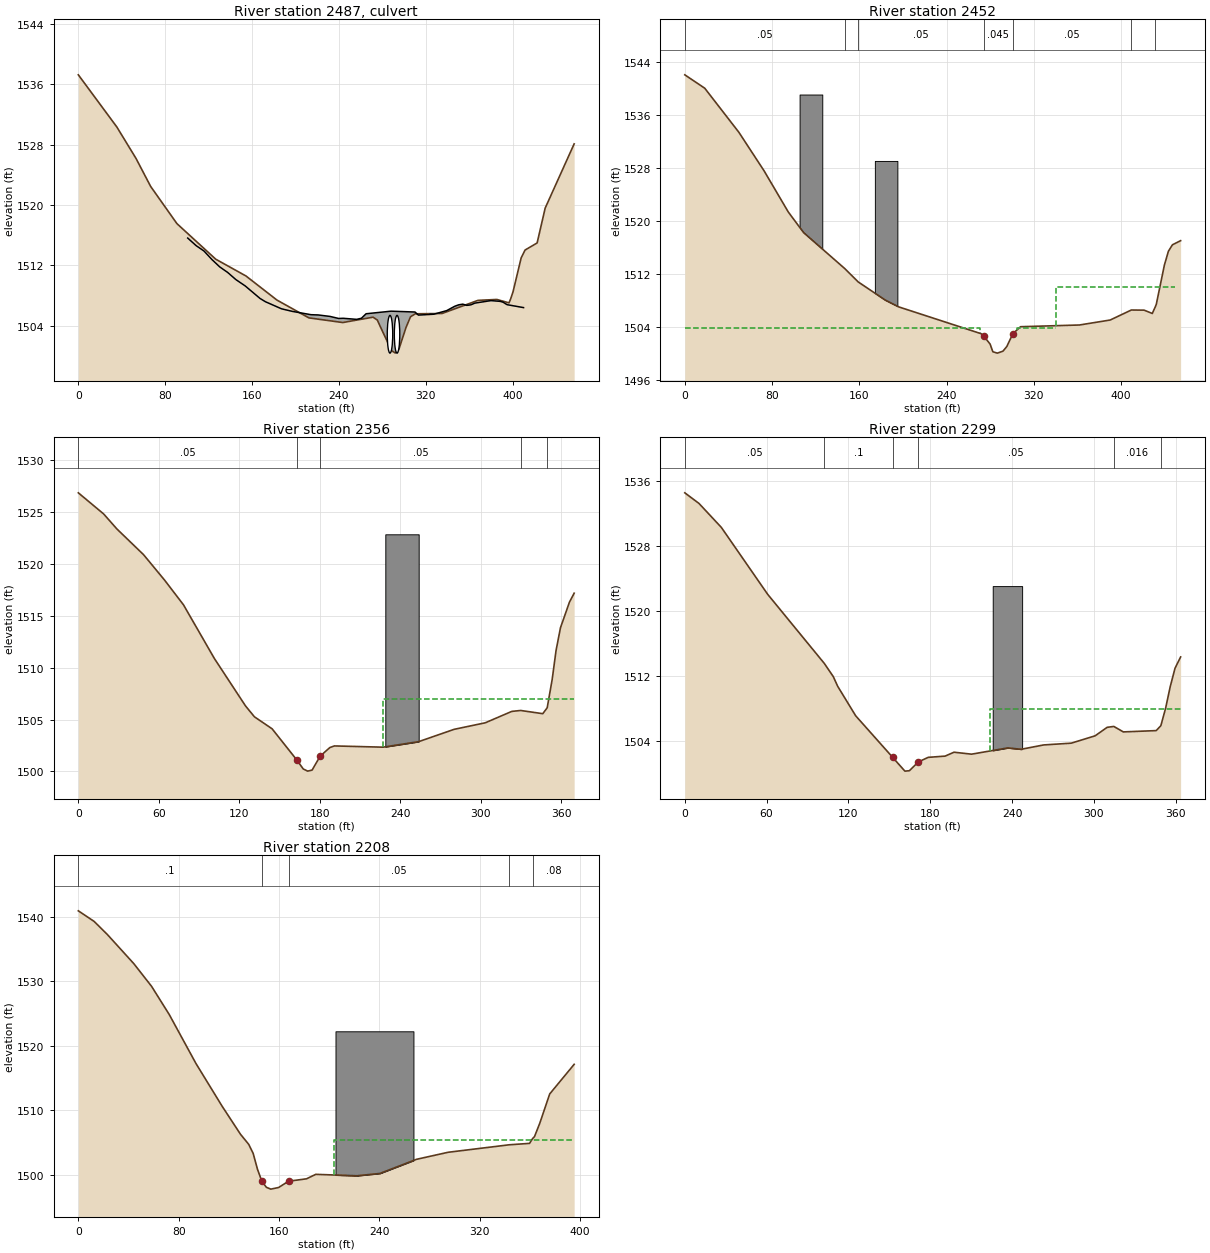
Type RM Length L Ch R = 2 ,2487    ,,,
BEGIN DESCRIPTION:
Viola Lane
Survey ID: BLC030
END DESCRIPTION:
Bridge Culvert--1,0,-1,-1, 0
Deck Dist Width WeirC Skew NumUp NumDn MinLoCord MaxHiCord MaxSubmerge Is_Ogee
9,14,2.6,0, 37, 37, , , 0.98, 0, 0,0,,
 100.738 108.497 115.747 122.996 130.246 137.496  145.13 153.664 167.326 172.258
 187.056 196.921 214.184 220.867 231.742 239.732 243.925 256.334 260.707     265
     288     310 313.149 327.331 339.207 346.623 350.331 354.039 357.747 359.399
 361.455 365.163 379.994 388.545 391.118 394.826     410
1515.6181514.6111513.8961512.7751511.7911511.0641510.1071509.2741507.6151507.183
1506.2441505.9061505.4641505.4291505.2341504.9621504.9861504.844 1504.991505.587
1505.9291505.8181505.4081505.5251506.0021506.5781506.7731506.857  1506.71506.726
1506.7691506.9961507.3291507.2281507.1191506.789  1506.4
                                                                                
                                                                                
                                                                                
                                                        
 100.738 108.497 115.747 122.996 130.246 137.496  145.13 153.664 167.326 172.258
 187.056 196.921 214.184 220.867 231.742 239.732 243.925 256.334 260.707     265
     288     310 313.149 327.331 339.207 346.623 350.331 354.039 357.747 359.399
 361.455 365.163 379.994 388.545 391.118 394.826     410
1515.6181514.6111513.8961512.7751511.7911511.0641510.1071509.2741507.6151507.183
1506.2441505.9061505.4641505.4291505.2341504.9621504.9861504.844 1504.991505.587
1505.9291505.8181505.4081505.5251506.0021506.5781506.7731506.857  1506.71506.726
1506.7691506.9961507.3291507.2281507.1191506.789  1506.4
                                                                                
                                                                                
                                                                                
                                                        
BR Coef=-1 , 1 , 0 ,, 0 ,,,0.8,0,1.2,0,
WSPro=,,,, 1 ,,,, 0 ,,,, 0 ,,,,-1 ,-1 ,-1 , 0 , 0 , 0 , 0 , 0
Culvert=1,5,,22,0.012,0.9,1,55,1,1500.368,287,1500.025,285,Culvert #1  , 0 ,6
     287     285
BC Culvert Barrel=1,Barrel1,0
Culvert Bottom n=0.012
Culvert=1,5,,22,0.012,0.9,1,55,1,1500.368,293.5,1500.025,291.5,Culvert #2  , 0 ,6
   293.5   291.5
BC Culvert Barrel=1,Barrel1,0
Culvert Bottom n=0.012
BC Design=,, 0 ,, 0 ,,,,,,
BC Use User HTab Curves=0
BC User HTab FreeFlow(D)= 0

Type RM Length L Ch R = 1 ,2452    ,103.1,96.5,68.1
BEGIN DESCRIPTION:
Channel burned from survey: 54089BLC028CD
END DESCRIPTION:
XS GIS Cut Line= 4
2039672.20914054224991.3732578862039454.19626619224888.951102153
2039398.59566737224839.9347847662039274.95749366224774.823557194
#Sta/Elev= 30
       0 1542.02    18.3    1540    49.6 1533.35    72.7 1527.54    94.9 1521.33
   108.9 1518.23   146.7 1512.79     159 1510.78   183.7 1508.05   196.2 1507.01
   271.7 1502.97   274.1 1502.62     280  1501.4   282.5 1500.24   286.61500.036
  291.77 1500.33  295.29 1501.03   300.9 1502.97   307.9 1504.02   361.9 1504.28
   390.1 1505.03   409.5 1506.54   421.2 1506.52   428.7 1506.02   431.4 1506.99
   432.4  1507.4   439.8 1513.31   443.5 1515.41   447.2 1516.38   454.7    1517
#Mann= 7 ,-1 , 0
       0     .05       0   146.7    .016       0     159     .05       0
   274.1    .045       0   300.9     .05       0   409.5    .016       0
   431.4     .08       0
#XS Ineff= 3 ,-1
       0   270.7  1503.8   304.6     340  1503.8     340     450    1510
Permanent Ineff=
       F       F       F
#Block Obstruct= 2 ,-1
  105.26  126.08 1539.05   174.3  194.95 1529.03
Bank Sta=274.1,300.9
XS Rating Curve= 0 ,0
Exp/Cntr(USF)=0,0
Exp/Cntr=0.5,0.3

Type RM Length L Ch R = 1 ,2356    ,57.2,56.2,59.3
XS GIS Cut Line= 2
2039648.09591507224812.0908432642039281.39930812224765.124775379
#Sta/Elev= 30
       0 1526.87    18.9 1524.83    28.8 1523.38    48.6 1520.91    64.2 1518.47
    78.4 1516.07   101.5 1510.88   124.7 1506.31   131.3 1505.27   144.5 1504.11
   162.7 1501.14   167.7 1500.24     171 1500.03   174.3 1500.13   180.3 1501.47
   187.5  1502.3   190.9 1502.46   227.2 1502.34   253.7 1502.87   280.2 1504.06
   303.4 1504.69   323.2 1505.79   329.8 1505.88   346.3 1505.57   349.6 1506.14
   353.3 1508.86   356.2 1511.66   359.5 1513.86   366.2 1516.33   369.7 1517.19
#Mann= 5 ,-1 , 0
       0     .05       0   162.7    .045       0   180.3     .05       0
   329.8    .016       0   349.6     .08       0
#XS Ineff= 2 , 0
                             227            1507
Permanent Ineff=
       F       F
#Block Obstruct= 1 ,-1
  228.89  253.78 1522.87
Bank Sta=162.7,180.3
XS Rating Curve= 0 ,0
Exp/Cntr(USF)=0,0
Exp/Cntr=0.3,0.1

Type RM Length L Ch R = 1 ,2299    ,95.3,91,79.9
XS GIS Cut Line= 3
2039649.61100829 224740.459740572039385.16565886 224731.98678671
2039290.83825611224762.039678222
#Sta/Elev= 30
       0 1534.49    10.4 1533.19    26.8 1530.25    60.8 1522.04   102.3 1513.57
   108.9 1511.95   112.1 1510.77   125.3 1507.15   152.51502.038   161.4 1500.36
   164.7 1500.41   171.2 1501.48   178.5 1502.05   190.9  1502.2   197.4 1502.68
   210.3 1502.44   236.9 1503.21   246.7 1503.04   263.1 1503.57   283.4 1503.79
   300.9 1504.69   309.7 1505.73   314.6 1505.84   321.6 1505.17   345.7 1505.33
   349.1 1505.93   352.6 1508.08     356 1510.74   359.5 1512.98   363.6 1514.36
#Mann= 6 ,-1 , 0
       0     .05       0   102.3      .1       0   152.5    .045       0
   171.2     .05       0   314.6    .016       0   349.1      .1       0
#XS Ineff= 2 , 0
                             224            1508
Permanent Ineff=
       F       F
#Block Obstruct= 1 ,-1
  225.81  247.38 1523.05
Bank Sta=152.5,171.2
XS Rating Curve= 0 ,0
Exp/Cntr(USF)=0,0
Exp/Cntr=0.3,0.1

Type RM Length L Ch R = 1 ,2208    ,181.5,169.3,151.6
XS GIS Cut Line= 4
2039634.54801087224588.0988271992039472.87635411224651.322380121
2039362.68673331 224705.51399691 2039282.1826437224763.127110884
#Sta/Elev= 30
       0 1540.92    12.6 1539.28    23.2 1537.24    44.3 1532.72    58.4 1529.22
    72.5 1524.85    93.8 1517.26   114.7 1510.63   129.3  1506.3   135.9 1504.72
   139.4 1503.34   142.9 1500.85   146.4 1498.98     150 1498.07   153.5 1497.79
   159.7 1498.04   167.6 1499.01     182 1499.39   189.3 1500.08   222.2 1499.86
   240.5 1500.22   269.7 1502.41   294.9  1503.5   343.6 1504.66   359.8 1504.88
   362.3 1505.63   363.8 1505.94     368 1508.01   375.9 1512.54   395.4 1517.13
#Mann= 5 ,-1 , 0
       0      .1       0   146.4    .045       0   167.6     .05       0
   343.6    .016       0   362.3     .08       0
#XS Ineff= 2 , 0
                             204         1505.45
Permanent Ineff=
       F       F
#Block Obstruct= 1 ,-1
  205.07  267.24 1522.25
Bank Sta=146.4,167.6
XS Rating Curve= 0 ,0
Exp/Cntr(USF)=0,0
Exp/Cntr=0.5,0.3