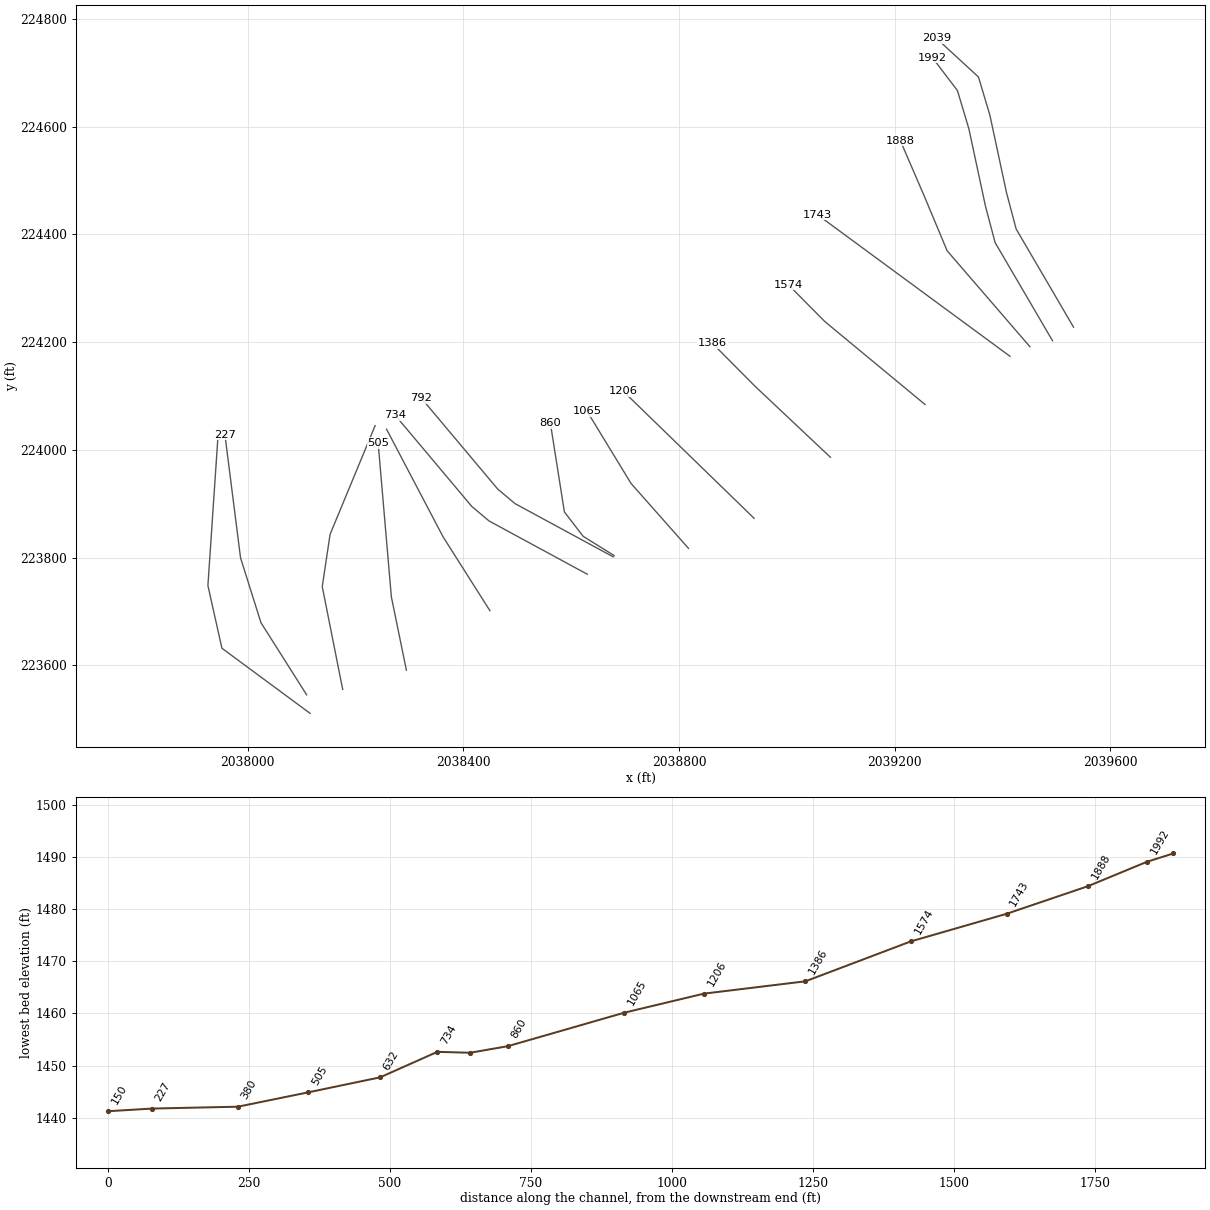
HEC-RAS study BLUELICK.prj: BLUELICK

--- BLUELICK.g01 (geometry) --- (continued)

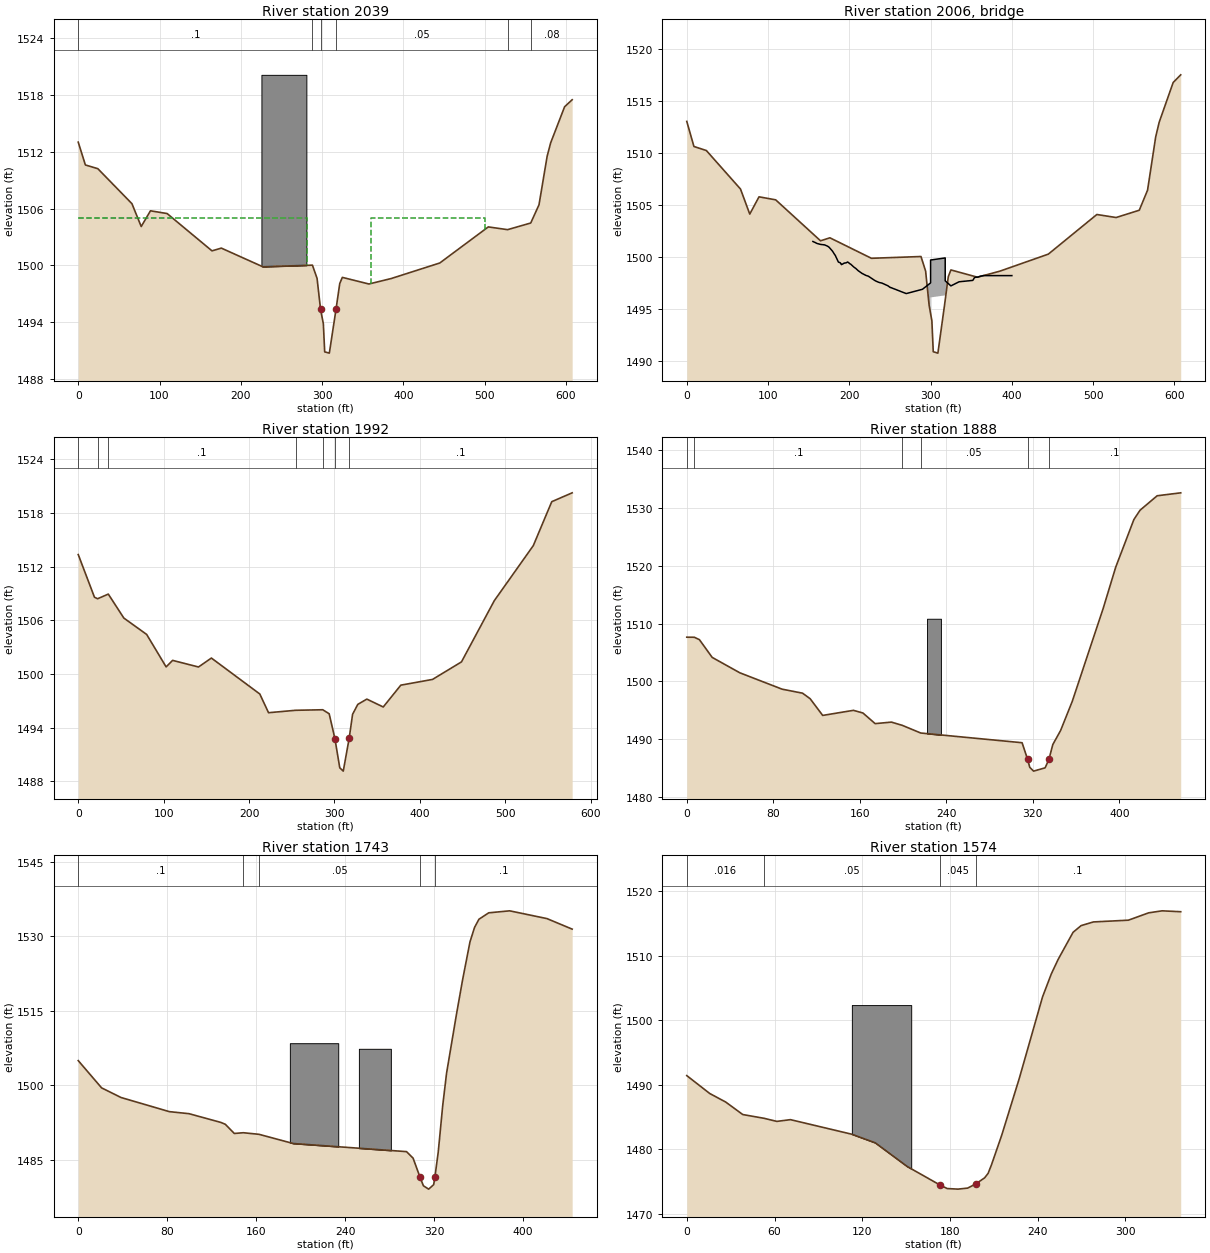
Type RM Length L Ch R = 1 ,2039    ,45.5,46.8,46.4
BEGIN DESCRIPTION:
Chanel burn based on survey: 54089BLC022BU
END DESCRIPTION:
XS GIS Cut Line= 6
 2039532.2161745224227.8148949082039425.72964751224409.898727322
2039407.84641397224477.367290225 2039376.9571924224621.246032802
2039355.82246185224691.9660927132039277.87685303224763.769984959
#Sta/Elev= 30
       0 1513.01     8.8  1510.6    24.1 1510.21    66.1 1506.51    77.5  1504.1
    88.9 1505.76   109.4 1505.47   164.6 1501.53   176.1 1501.82   227.2 1499.85
   288.2 1500.02   293.9 1498.62   298.2 1495.34   301.6 1493.84  303.281490.864
     3091490.731   317.2 1495.36   321.8 1498.08     325 1498.73   357.7 1498.03
   385.2 1498.61   444.9 1500.25   504.6 1504.06   528.3 1503.77   556.8 1504.47
     567  1506.4     577 1511.52   581.3 1512.93   598.5 1516.75   607.8 1517.49
#Mann= 6 ,-1 , 0
       0      .1       0   288.2     .01       0   298.2    .045       0
   317.2     .05       0   528.3    .016       0   556.8     .08       0
#XS Ineff= 4 ,-1
       0     281    1505     281     288 1497.24     330     360 1497.49
     360     500    1505
Permanent Ineff=
       F       F       F       F
#Block Obstruct= 1 ,-1
  225.41  280.74 1520.12
Bank Sta=298.2,317.2
XS Rating Curve= 0 ,0
Exp/Cntr(USF)=0,0
Exp/Cntr=0.5,0.3

Type RM Length L Ch R = 3 ,2006    ,,,
BEGIN DESCRIPTION:
Barger Springs Rd
Survey ID: BLC020
Included 2.2 ft railing
END DESCRIPTION:
Bridge Culvert--1,0,-1,-1, 0
Deck Dist Width WeirC Skew NumUp NumDn MinLoCord MaxHiCord MaxSubmerge Is_Ogee
22,20,2.6,0, 160, 116, , , 0.98, 0, 0,0,,
 155.198 156.094 156.094 157.596 159.514 159.895 159.895 159.994 160.165 160.165
 162.393 163.695 163.695 164.791 166.664 166.664 167.189 167.496 167.496 168.668
 169.587 171.297 171.297 171.985 173.163 173.163 174.384 175.098 175.098 176.782
 177.823 178.898 178.898  179.18 179.662 179.662 181.578 182.699 182.699 183.976
 186.161 186.161 186.375   186.5   186.5 186.977 188.773   190.3   190.3 191.171
 192.659 192.659 193.569 194.101 194.101 195.967 196.132 197.902 197.902 198.365
 199.158 199.158 200.764 201.702 201.702 203.162 205.286 205.503 205.503  205.56
 205.657 205.657 207.958 209.304 209.304 210.356 210.936 210.936  212.54  212.54
 212.839 212.963 212.963 213.265 215.349 215.783 215.783 216.484 216.484 218.001
 218.489 219.878 219.878 220.684 223.108 223.272 223.272 223.367 223.728 223.728
  226.05 226.666 226.666 227.726 228.733  230.06  230.06 231.416 232.344 233.454
 233.454 234.099 236.533 236.533 236.782 236.848 236.848 236.962 239.465 240.243
 240.243  241.58 242.148 243.637 243.637 244.831 246.199 247.031 247.031 247.514
 249.338 249.338 250.197 250.425 250.425 250.817     270     290     300     300
     318     318     325     335     352 354.111 354.852 354.852 355.999 356.873
 358.208 358.208 359.636 360.272 361.563 361.563 362.398 364.545 364.919     400
1501.4651501.4341501.4341501.3811501.3021501.2871501.2871501.2831501.2771501.277
1501.2241501.2021501.2021501.1831501.1631501.1631501.1631501.1641501.1641501.147
1501.139 1501.08 1501.081501.0481501.0171501.0171500.9511500.9131500.9131500.754
1500.6691500.5771500.5771500.5461500.4931500.4931500.2511500.1311500.1311499.921
1499.5471499.5471499.5131499.4971499.4971499.4731499.4241499.2441499.244 1499.27
1499.3341499.3341499.3881499.3891499.3891499.4071499.4161499.4921499.4921499.472
1499.4271499.4271499.3181499.2841499.2841499.1781499.0231499.0071499.0071499.005
    1499    14991498.8731498.7721498.7721498.6981498.6571498.6571498.5661498.566
1498.5511498.5441498.5441498.5281498.4081498.3881498.3881498.3641498.3641498.299
1498.2781498.2191498.2191498.1961498.1391498.1351498.1351498.1311498.1121498.112
1497.9861497.9521497.9521497.8951497.8471497.7681497.7681497.7121497.6741497.629
1497.6291497.6061497.5311497.5311497.5241497.5221497.522 1497.521497.4731497.463
1497.4631497.4151497.3941497.3411497.3411497.3031497.2521497.2241497.2241497.205
1497.0931497.0931497.0481497.0361497.0361497.0441496.456 1496.871497.4851499.685
1499.8851497.6851497.1951497.5891497.7261498.0041498.0151498.0151498.0261498.031
1498.0471498.0471498.0851498.1011498.1341498.1341498.1411498.1811498.1851498.185
                                                                                
                                                                                
                                                                                
                                                                                
                                                                                
                                                                                
                                                                                
                                                                                
                                                                                
                                                                                
                                                                                
                                                                                
                                                                                
                                                                        1496.085
1496.285
                                                                                
   186.5 186.977 188.773   190.3   190.3 191.171 192.659 192.659 193.569 194.101
 194.101 195.967 196.132 197.902 197.902 198.365 199.158 199.158 200.764 201.702
 201.702 203.162 205.286 205.503 205.503  205.56 205.657 205.657 207.958 209.304
 209.304 210.356 210.936 210.936  212.54  212.54 212.839 212.963 212.963 213.265
 215.349 215.783 215.783 216.484 216.484 218.001 218.489 219.878 219.878 220.684
 223.108 223.272 223.272 223.367 223.728 223.728  226.05 226.666 226.666 227.726
 228.733  230.06  230.06 231.416 232.344 233.454 233.454 234.099 236.533 236.533
 236.782 236.848 236.848 236.962 239.465 240.243 240.243  241.58 242.148 243.637
 243.637 244.831 246.199 247.031 247.031 247.514 249.338 249.338 250.197 250.425
 250.425 250.817     270     290     300     300     318     318     325     335
     352 354.111 354.852 354.852 355.999 356.873 358.208 358.208 359.636 360.272
 361.563 361.563 362.398 364.545 364.919     400
1499.4971499.4731499.4241499.2441499.244 1499.271499.3341499.3341499.3881499.389
1499.3891499.4071499.4161499.4921499.4921499.4721499.4271499.4271499.3181499.284
1499.2841499.1781499.0231499.0071499.0071499.005    1499    14991498.8731498.772
1498.7721498.6981498.6571498.6571498.5661498.5661498.5511498.5441498.5441498.528
1498.4081498.3881498.3881498.3641498.3641498.2991498.2781498.2191498.2191498.196
1498.1391498.1351498.1351498.1311498.1121498.1121497.9861497.9521497.9521497.895
1497.8471497.7681497.7681497.7121497.6741497.6291497.6291497.6061497.5311497.531
1497.5241497.5221497.522 1497.521497.4731497.4631497.4631497.4151497.3941497.341
1497.3411497.3031497.2521497.2241497.2241497.2051497.0931497.0931497.0481497.036
1497.0361497.0441496.456 1496.871497.4851499.6851499.8851497.6851497.1951497.589
1497.7261498.0041498.0151498.0151498.0261498.0311498.0471498.0471498.0851498.101
1498.1341498.1341498.1411498.1811498.1851498.185
                                                                                
                                                                                
                                                                                
                                                                                
                                                                                
                                                                                
                                                                                
                                                                                
                                                                                
                                        1496.0851496.285
                                                                                
                                                
BR Coef=-1 , 1 , 0 ,, 0 ,,,0.8,0,1.2,0,
WSPro=,,,, 1 ,,,, 0 ,,,, 0 ,,,,-1 ,-1 ,-1 , 0 , 0 , 0 , 0 , 0
BR U #Sta/Elev= 30
       0 1513.01     8.8  1510.6    24.1 1510.21    66.1 1506.51    77.5  1504.1
    88.9 1505.76   109.4 1505.47   164.6 1501.53   176.1 1501.82   227.2 1499.85
   288.2 1500.02   293.9 1498.62   298.2 1495.34   301.6 1493.84  303.281490.864
     3091490.731   317.2 1495.36   321.8 1498.08     325 1498.73   357.7 1498.03
   385.2 1498.61   444.9 1500.25   504.6 1504.06   528.3 1503.77   556.8 1504.47
     567  1506.4     577 1511.52   581.3 1512.93   598.5 1516.75   607.8 1517.49
BR U #Mann= 6
       0      .1   288.2     .01   298.2     .04   317.2     .05   528.3    .016
   556.8     .08
BR D #Sta/Elev= 30
       0 1513.34      19 1508.57    22.7  1508.4    35.2 1508.92    53.4 1506.24
    80.1 1504.41   102.9 1500.78   110.5 1501.51   140.8 1500.77   155.9 1501.77
   212.6 1497.75   222.8 1495.66   254.6 1495.93   286.3 1495.99   293.8 1495.54
   300.5 1492.77   306.21489.503  310.291489.129   317.2 1492.79   321.2 1495.48
   327.3 1496.59   337.9 1497.18   357.1  1496.3   377.7 1498.74   414.8 1499.38
   448.7 1501.34   487.1 1508.18   532.8 1514.34   554.4 1519.25   578.3 1520.24
BR D #Mann= 7
       0      .1    22.7    .016    35.2      .1   254.6    .016   286.3     .05
   300.5     .04   317.2      .1
BC Design=,, 0 ,, 0 ,,,,,,
BC Use User HTab Curves=0
BC User HTab FreeFlow(D)= 0

Type RM Length L Ch R = 1 ,1992    ,102,104.7,107.6
BEGIN DESCRIPTION:
Channel burn based on survey: 54089BLC018BD
END DESCRIPTION:
XS GIS Cut Line= 6
2039493.19821041224202.6157931012039386.71168342224384.699625515
2039368.82844988224452.1681884182039337.93922831224596.046930995
2039316.80449776224666.766990906 2039270.4706654224727.732559794
#Sta/Elev= 30
       0 1513.34      19 1508.57    22.7  1508.4    35.2 1508.92    53.4 1506.24
    80.1 1504.41   102.9 1500.78   110.5 1501.51   140.8 1500.77   155.9 1501.77
   212.6 1497.75   222.8 1495.66   254.6 1495.93   286.3 1495.99   293.8 1495.54
   300.5 1492.77   306.21489.503  310.291489.129   317.2 1492.79   321.2 1495.48
   327.3 1496.59   337.9 1497.18   357.1  1496.3   377.7 1498.74   414.8 1499.38
   448.7 1501.34   487.1 1508.18   532.8 1514.34   554.4 1519.25   578.3 1520.24
#Mann= 7 ,-1 , 0
       0      .1       0    22.7    .016       0    35.2      .1       0
   254.6    .016       0   286.3     .05       0   300.5    .045       0
   317.2      .1       0
#XS Ineff= 2 , 0
         297.333  1493.7 320.667          1493.7
Permanent Ineff=
       F       F
Bank Sta=300.5,317.2
XS Rating Curve= 0 ,0
Exp/Cntr(USF)=0,0
Exp/Cntr=0.5,0.3

Type RM Length L Ch R = 1 ,1888    ,138.2,144.4,150.7
XS GIS Cut Line= 4
 2039451.1997074 224191.596831022039297.65679316224369.525972813
2039256.10988695224468.877270261 2039210.9502063224573.647729388
#Sta/Elev= 30
       0 1507.64       7 1507.63    11.7 1507.21    23.5 1504.14    49.1 1501.47
    88.1 1498.64   107.1 1497.94   114.1 1496.98   125.7 1494.09   154.1 1494.97
   162.9 1494.51   174.2 1492.67   189.3 1492.93   199.3 1492.37   216.4 1491.04
   310.1 1489.36   315.2 1486.47   317.2  1485.1   320.7 1484.44   331.4 1485.01
     335 1486.53   338.5 1489.04   345.7 1491.47   356.4 1496.48     385 1512.57
   396.7 1519.78   413.5 1528.03   419.2 1529.64     435 1532.14   456.8 1532.65
#Mann= 6 ,-1 , 0
       0    .016       0       7      .1       0   199.3    .016       0
   216.4     .05       0   315.2    .045       0     335      .1       0
#Block Obstruct= 1 ,-1
  222.21  235.02 1510.84
Bank Sta=315.2,335
XS Rating Curve= 0 ,0
Exp/Cntr(USF)=0,0
Exp/Cntr=0.3,0.1

Type RM Length L Ch R = 1 ,1743    ,173.7,169.6,164.4
XS GIS Cut Line= 2
2039414.34940798 224173.713597482039056.68473717224436.723577633
#Sta/Elev= 30
       0 1504.97      21 1499.49    38.5 1497.55    81.9 1494.71    99.6  1494.3
   128.1 1492.55   132.2 1492.17   140.3 1490.32   148.4 1490.47   162.5 1490.15
   193.3  1488.3   295.1 1486.67     301 1485.36   307.3 1481.49   310.3  1479.8
     315 1479.13   319.5 1480.03  320.651481.645   323.6 1486.56   327.6 1495.86
   331.1 1502.46   339.9 1514.16   345.5 1521.22   352.1 1528.81   356.2 1531.73
   360.2  1533.4     369 1534.69   387.8 1535.09   421.3 1533.53     444 1531.41
#Mann= 5 ,-1 , 0
       0      .1       0   148.4    .016       0   162.5     .05       0
   307.3    .045       0  320.65      .1       0
#Block Obstruct= 2 ,-1
  190.22  233.72 1508.47  252.27  281.01 1507.35
Bank Sta=307.3,320.65
XS Rating Curve= 0 ,0
Exp/Cntr(USF)=0,0
Exp/Cntr=0.3,0.1

Type RM Length L Ch R = 1 ,1574    ,183.1,187.1,179.6
XS GIS Cut Line= 3
2039256.65180312224084.2974297762039070.50359945224238.382260182
2039002.84150479224306.713459583
#Sta/Elev= 30
       0 1491.42    15.7 1488.65    26.6 1487.33    38.3 1485.39    52.8 1484.81
    61.6 1484.33    70.9  1484.6   112.9 1482.34   128.9 1481.01   150.7 1477.35
   173.4 1474.45   178.1 1473.93   185.5 1473.84   192.1    1474   197.6 1474.64
   203.7 1475.59   206.1 1476.29   208.4 1477.62   215.4  1482.2   227.4 1490.99
   243.3 1503.61   249.3 1507.17     254 1509.43   264.2 1513.62   269.7 1514.65
   278.1 1515.22     302 1515.49   315.9 1516.63   325.1 1516.94   337.8  1516.8
#Mann= 4 ,-1 , 0
       0    .016       0    52.8     .05       0   173.4    .045       0
   197.6      .1       0
#Block Obstruct= 1 ,-1
  112.89  153.49 1502.34
Bank Sta=173.4,197.6
XS Rating Curve= 0 ,0
Exp/Cntr(USF)=0,0
Exp/Cntr=0.3,0.1

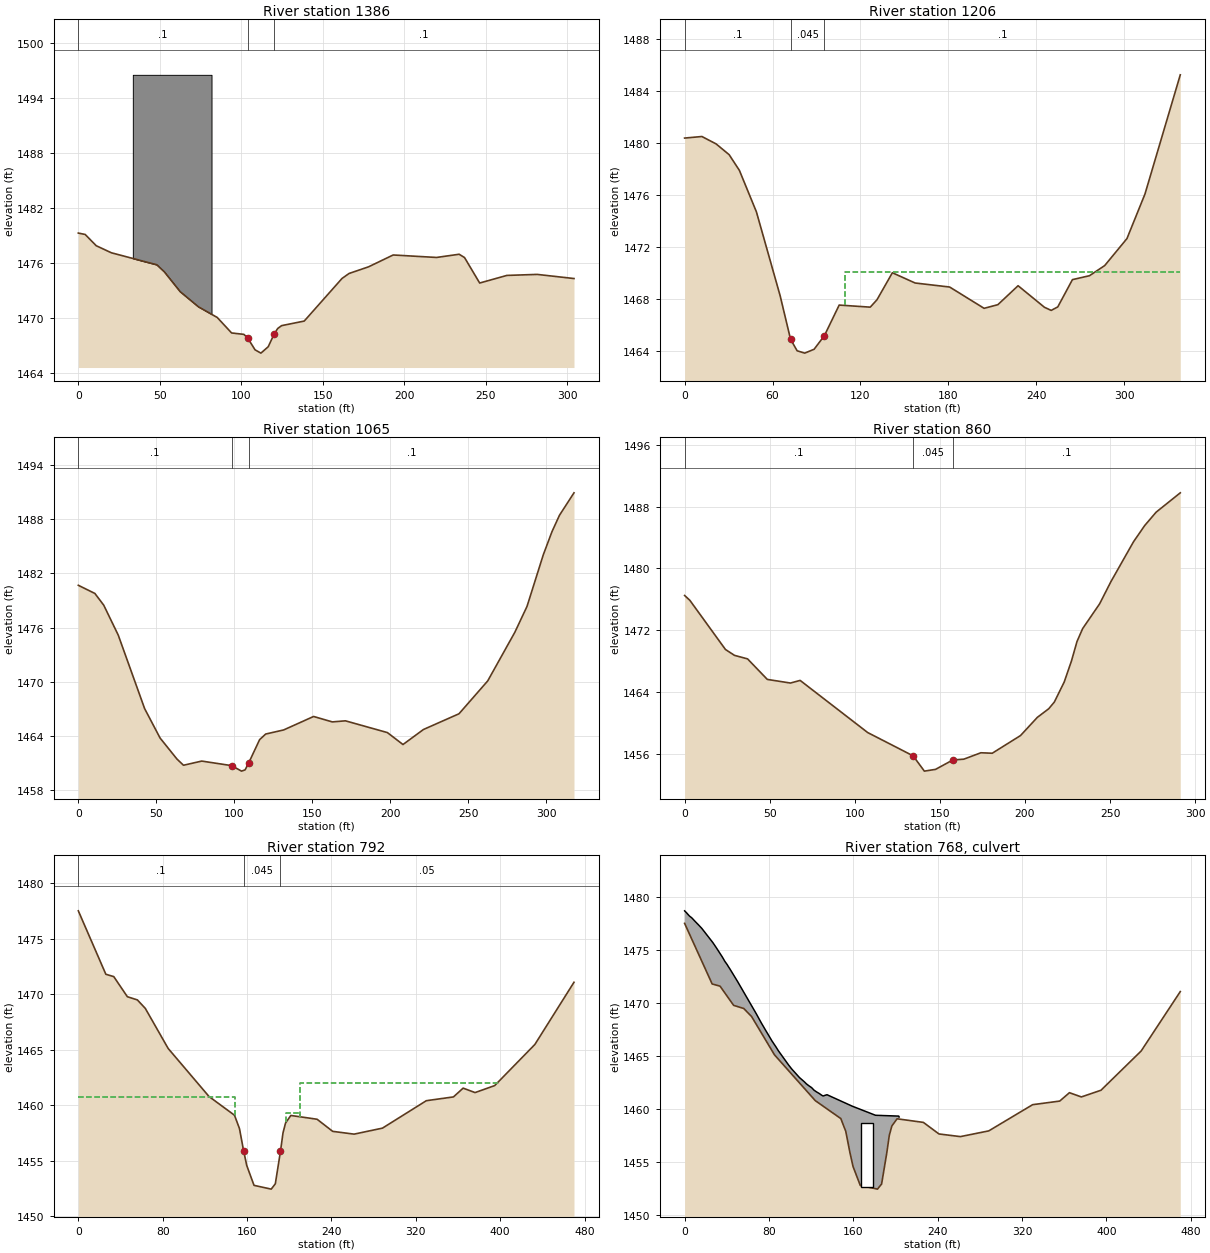
Type RM Length L Ch R = 1 ,1386    ,179.1,180,178.2
XS GIS Cut Line= 3
2039081.07096472223986.3912421092038941.25659341224118.076870909
2038862.15703936224197.721648456
#Sta/Elev= 30
       0 1479.27     4.2 1479.12      11 1477.89    20.3 1477.12    48.2 1475.81
    52.8 1475.04    62.5 1472.88    73.7 1471.23    85.3 1470.06    94.1 1468.37
   101.6 1468.22   103.9 1467.84   108.5 1466.53   112.1 1466.17   116.6 1466.87
   120.1 1468.21   122.4 1468.86   124.8 1469.17   138.7 1469.67   161.9 1474.32
   166.2 1474.86   178.2 1475.59   193.3 1476.88   219.9 1476.61   233.8 1476.96
   237.1  1476.6   246.4 1473.82   263.1 1474.65   281.7 1474.76   304.3 1474.31
#Mann= 3 , 0 , 0
       0      .1       0   103.9    .045       0   120.1      .1       0
#Block Obstruct= 1 ,-1
   33.46   81.77 1496.54
Bank Sta=103.9,120.1
XS Rating Curve= 0 ,0
Exp/Cntr(USF)=0,0
Exp/Cntr=0.3,0.1

Type RM Length L Ch R = 1 ,1206    ,129,141.6,134.1
XS GIS Cut Line= 2
2038939.44123646223873.1504365832038696.73684375224108.827618104
#Sta/Elev= 30
       0 1480.36    11.8 1480.48    21.5 1479.91    30.4 1479.08    37.4 1477.87
      49 1474.68    65.2 1468.22    72.3 1464.87    76.8 1463.98      82  1463.8
    88.4  1464.1    95.41465.145   105.5  1467.5   126.7 1467.34   131.3 1467.91
   141.8 1469.99   157.3  1469.2   180.9 1468.89   204.4 1467.25   213.8 1467.53
   227.6 1468.99   245.6 1467.33   250.2 1467.09   254.7 1467.36   264.7 1469.46
   276.3 1469.76   286.7 1470.54   301.9 1472.62   314.2 1476.05   338.3 1485.23
#Mann= 3 , 0 , 0
       0      .1       0    72.3    .045       0    95.4      .1       0
#XS Ineff= 2 , 0
       0                   109.3       0 1470.05
Permanent Ineff=
       F       F
Bank Sta=72.3,95.4
XS Rating Curve= 0 ,0
Exp/Cntr(USF)=0,0
Exp/Cntr=0.3,0.1

Type RM Length L Ch R = 1 ,1065    ,202.3,205.3,181.3
XS GIS Cut Line= 3
2038817.69970713223817.3133977252038711.21318013223937.618786999
2038629.48657731224071.724022827
#Sta/Elev= 30
       0 1480.67    10.6 1479.77    16.3 1478.47    25.6 1475.16    42.5 1467.04
    52.4 1463.79    63.2 1461.47    67.4 1460.78    79.1 1461.24    98.2 1460.74
   104.6 1460.13   106.9 1460.27   109.3 1461.07   116.2 1463.61   120.1 1464.23
   131.6 1464.68   150.8 1466.17   162.8 1465.57   171.2 1465.69   198.1 1464.39
   208.1 1463.07   221.2 1464.73     244 1466.47   262.4  1470.1   279.8 1475.48
   287.6 1478.34     298 1484.03   303.6  1486.6   308.4 1488.41   317.7 1490.89
#Mann= 3 , 0 , 0
       0      .1       0    98.2    .045       0   109.3      .1       0
#XS Ineff= 2 , 0
                          148.51         1465.93
Permanent Ineff=
       F       F
Bank Sta=98.2,109.3
XS Rating Curve= 0 ,0
Exp/Cntr(USF)=0,0
Exp/Cntr=0.3,0.1

Type RM Length L Ch R = 1 ,860     ,38.7,67.3,88.3
XS GIS Cut Line= 4
2038679.86037638223803.9226763122038622.26108234223839.655571687
 2038587.4368178223884.863248054 2038561.4633193224049.307267347
#Sta/Elev= 30
       0  1476.5     3.1 1475.87      24  1469.5    29.3 1468.74      37 1468.28
    48.6 1465.62    62.2 1465.15    67.9 1465.49   107.6 1458.73   134.3 1455.71
   140.9 1453.73   147.5 1453.96   157.61455.173   164.1 1455.28   174.1 1456.11
   180.8 1456.05   197.4 1458.34   207.3  1460.7     214 1461.82   217.3 1462.69
   223.1 1465.29   227.3 1467.98   230.6 1470.53   233.9  1472.2   243.9 1475.42
   250.5 1478.28   263.8 1483.46   270.4 1485.57   277.1  1487.3   291.3 1489.81
#Mann= 3 ,-1 , 0
       0      .1       0   134.3    .045       0   157.6      .1       0
Bank Sta=134.3,157.6
XS Rating Curve= 0 ,0
Exp/Cntr(USF)=0,0
Exp/Cntr=0.8,0.6

Type RM Length L Ch R = 1 ,792     ,63.4,58.3,58.3
XS GIS Cut Line= 4
2038677.94516425223801.6255366412038495.78004441 223900.38975824
2038463.59022404223927.4584708272038321.66237966224096.455027786
#Sta/Elev= 30
       0  1477.5    26.1 1471.79    33.6 1471.58    46.5 1469.77      56 1469.48
    63.5 1468.72    85.2 1465.11   123.9 1460.79   148.1  1459.1   152.8  1457.9
   156.7 1455.92   159.7 1454.58   166.6 1452.79   182.9 1452.45   186.8 1452.93
   191.7 1455.86   194.1 1457.52   196.5  1458.4   201.5 1459.08   226.4 1458.74
   241.2 1457.65   261.5  1457.4   288.4 1457.94     330 1460.41   355.7 1460.75
   364.9 1461.54   376.2 1461.14   394.8 1461.77   432.9 1465.47     470 1471.07
#Mann= 3 ,-1 , 0
       0      .1       0   156.7    .045       0   191.7     .05       0
#XS Ineff= 3 ,-1
       0     149  1460.7     197     210 1459.33     210     400    1462
Permanent Ineff=
       F       F       F
Bank Sta=156.7,191.7
XS Rating Curve= 0 ,0
Exp/Cntr(USF)=0,0
Exp/Cntr=0.8,0.6

Type RM Length L Ch R = 2 ,768     ,,,
BEGIN DESCRIPTION:
Doc Fox Rd
Survey ID: BLC010
END DESCRIPTION:
Bridge Culvert--1,0,-1,-1, 0
Deck Dist Width WeirC Skew NumUp NumDn MinLoCord MaxHiCord MaxSubmerge Is_Ogee
19,12,2.6,0, 186, 111, , , 0.98, 0, 0,0,,
       0    .682    .682   1.779   3.802   3.802   4.199   4.414   4.414   5.138
   6.619   8.146   8.146   9.039  10.686  10.686  11.459  11.878  11.878  13.289
  13.879   15.61   15.61  16.298  17.569  17.569  18.718  19.342  19.342  21.138
  21.441  23.074  23.074  23.558  24.453  24.453  25.978  26.806  26.806  28.398
  29.592  30.538  30.538  30.818  31.336  31.336  33.238   34.27   34.27  35.658
  37.744  38.002  38.002  38.078   38.22   38.22  40.498  41.734  41.734  42.918
  45.103  45.103  45.338  45.466  45.466  45.895  47.758  49.198  49.198  50.178
  51.986  51.986  52.598   52.93   52.93  54.047  55.018  56.662  56.662  57.438
   58.87   58.87  59.858  60.394  60.394  62.198  62.278  64.126  64.126  64.698
  65.753  65.753  67.118  67.858  67.858  69.538   70.35   71.59   71.59  71.958
  72.637  72.637  74.378  75.322  75.322  76.798  78.501  79.054  79.054  79.218
   79.52   79.52  81.638  82.786  82.786  84.058  86.404  86.404  86.478  86.518
  86.518  86.653  88.898   90.25   90.25  91.318  93.287  93.287  93.738  93.982
  93.982  94.804  96.158  97.714  97.714  98.578 100.171 100.171 100.998 101.446
 101.446 102.956 103.418 105.178 105.178 105.837 107.054 107.054 108.257  108.91
  108.91 110.677 111.107 112.642 112.642 113.097 113.938 113.938 115.517 116.374
 116.374 117.937 119.259 120.106 120.106 120.357 120.821 120.821 122.777 123.838
 123.838 125.197  127.41  127.57  127.57 127.617 127.705 127.705 130.037 131.302
     135     159     181     203 203.423 203.423
1478.6831478.6161478.6161478.504 1478.27 1478.271478.231 1478.21 1478.211478.149
1478.0381477.8741477.8741477.7851477.6111477.6111477.5371477.4931477.4931477.348
1477.2891477.1021477.1021477.0281476.8671476.8671476.7271476.6541476.6541476.431
1476.3921476.1811476.1811476.1191475.9981475.9981475.7951475.6851475.685 1475.46
1475.2761475.1341475.1341475.0891475.0071475.0071474.7181474.5681474.5681474.348
1473.9921473.9481473.9481473.9361473.9121473.9121473.5931473.3881473.3881473.212
1472.8581472.8581472.8231472.8031472.8031472.733 1472.441472.1951472.1951472.028
 1471.72 1471.721471.6151471.5591471.5591471.3691471.2041470.9241470.9241470.789
1470.5291470.529 1470.361470.2781470.2781469.9881469.9751469.6691469.669 1469.57
 1469.38 1469.381469.1311468.9961468.9961468.6891468.5411468.3151468.315 1468.25
1468.1321468.1321467.8291467.6771467.6771467.4271467.1381467.0441467.0441467.017
1466.9651466.9651466.6011466.4261466.4261466.2371465.8891465.8891465.8771465.871
1465.8711465.8511465.4941465.3051465.3051465.1521464.8681464.868  1464.81464.769
1464.7691464.6571464.4741464.2631464.2631464.1541463.9511463.9511463.8391463.789
1463.7891463.6231463.5721463.3781463.3781463.3111463.1711463.1711463.0271462.966
1462.9661462.8081462.7731462.6431462.6431462.6061462.5271462.5271462.369  1462.3
  1462.31462.1861462.0991462.0411462.0411462.0211461.9771461.9771461.7721461.695
1461.6951461.608 1461.481461.4711461.4711461.4681461.4631461.4631461.2971461.231
 1461.351460.2671459.4121459.3341459.2491459.249
                                                                                
                                                                                
                                                                                
                                                                                
                                                                                
                                                                                
                                                                                
                                                                                
                                                                                
                                                                                
                                                                                
                                                                                
                                                                                
                                                                                
                                                                                
                                                                                
                                                                                
                                                                                
                                                
 105.178 105.178 105.837 107.054 107.054 108.257  108.91  108.91 110.677 111.107
 112.642 112.642 113.097 113.938 113.938 115.517 116.374 116.374 117.937 119.259
 120.106 120.106 120.357 120.821 120.821 122.777 123.838 123.838 125.197  127.41
  127.57  127.57 127.617 127.705 127.705 130.037 131.302     135     159     181
     203 203.423 203.423 205.056 205.942 205.942 207.216 207.216  207.47 209.742
 209.742 209.821 209.821  209.83 209.838 209.838 209.925 212.159 214.124 214.124
 214.487 214.919 214.919 216.816 218.411 218.411 219.144 220.016 220.016 221.473
 222.698 222.698 223.801 225.114 225.114  226.13 226.984 226.984 228.458 230.212
 230.212 230.787 231.271 231.271 233.115 235.309 235.309 235.444 235.557 235.557
  236.87 237.773 239.844 239.844 240.101 240.407 240.407  242.43 244.131 244.131
 244.758 245.504 245.504 247.087 248.417 248.417 249.415 250.602 250.602 251.744
     270
1463.3781463.3781463.3111463.1711463.1711463.0271462.9661462.9661462.8081462.773
1462.6431462.6431462.6061462.5271462.5271462.369  1462.3  1462.31462.1861462.099
1462.0411462.0411462.0211461.9771461.9771461.7721461.6951461.6951461.608 1461.48
1461.4711461.4711461.4681461.4631461.4631461.2971461.231 1461.351460.2671459.412
1459.3341459.2491459.2491459.2981459.3241459.3241459.3241459.3241459.3251459.313
1459.3131459.3131459.3131459.3131459.3131459.3131459.3121459.2861459.2761459.276
1459.2731459.2641459.2641459.1761459.1231459.1231459.0911459.0471459.0471458.973
1458.9361458.936 1458.911458.8711458.8711458.8341458.7981458.7981458.7081458.578
1458.5781458.5371458.5051458.5051458.379 1458.23 1458.231458.2181458.2071458.207
1458.0851458.0011457.8091457.809 1457.791457.7731457.7731457.6821457.6051457.605
1457.5741457.5431457.5431457.4951457.4641457.4641457.4411457.4221457.4221457.406
    1456
                                                                                
                                                                                
                                                                                
                                                                                
                                                                                
                                                                                
                                                                                
                                                                                
                                                                                
                                                                                
                                                                                
        
BR Coef=-1 , 1 , 0 ,, 0 ,,,0.8,0,1.2,0,
WSPro=,,,, 1 ,,,, 0 ,,,, 0 ,,,,-1 ,-1 ,-1 , 0 , 0 , 0 , 0 , 0
Culvert=2,6,12,31,0.012,0.2,1,57,1,1452.642,173,1452.511,178,Culvert #1  , 0 ,14
     173     178
BC Culvert Barrel=1,Barrel1,0
Culvert Bottom n=0.012
BC Design=,, 0 ,, 0 ,,,,,,
BC Use User HTab Curves=0
BC User HTab FreeFlow(D)= 0

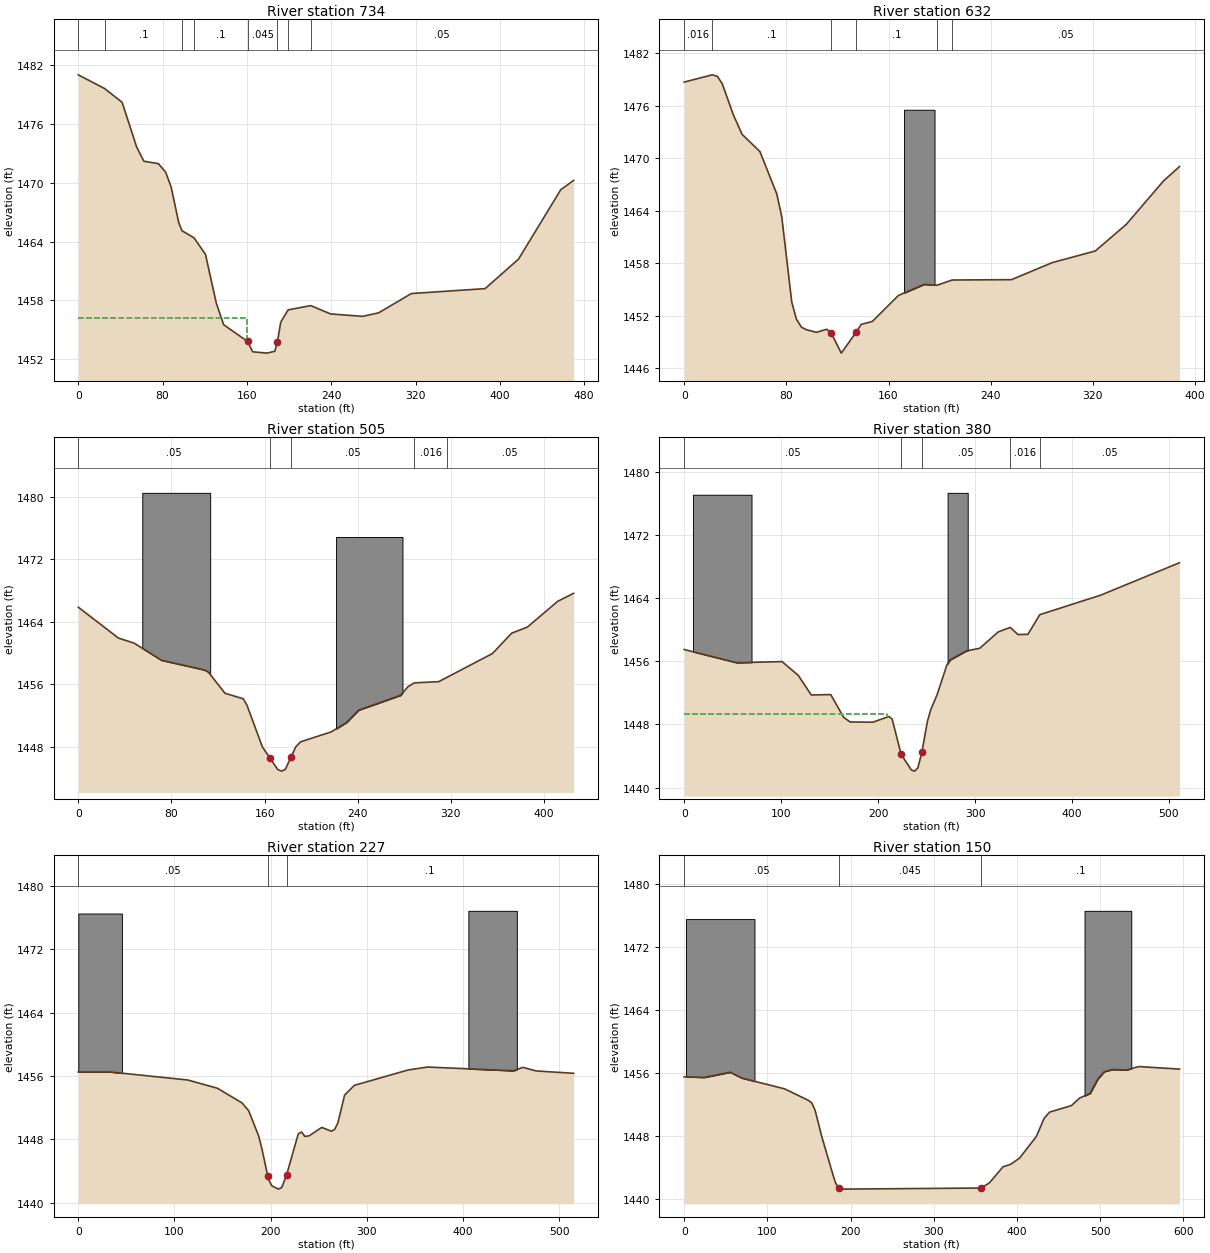
Type RM Length L Ch R = 1 ,734     ,117.5,101.5,90.5
XS GIS Cut Line= 4
2038629.87990974223769.362557585 2038447.7147899223868.126779185
2038415.52496952223895.1954917712038273.59712515 224064.19204873
#Sta/Elev= 30
       0 1481.04    25.1 1479.63    41.6 1478.23    55.3 1473.69    62.2 1472.22
      76 1471.97    82.9  1471.1    88.1 1469.58    95.3 1465.95    98.3 1465.13
   109.8  1464.4   120.7  1462.7     131 1457.71   137.9 1455.53   160.6 1453.82
  165.52 1452.76   179.21452.626  186.51 1452.82  188.92 1453.77   192.1 1455.79
   199.1 1457.04   220.6 1457.48   239.3 1456.63   269.7 1456.38     285 1456.74
   316.1 1458.71     386 1459.21   417.7 1462.22   457.8 1469.31     470 1470.26
#Mann= 8 ,-1 , 0
       0    .016       0    25.1      .1       0    98.3    .016       0
   109.8      .1       0   160.6    .045       0  188.92      .1       0
   199.1    .016       0   220.6     .05       0
#XS Ineff= 2 , 0
             160 1456.23   193.3          1455.1
Permanent Ineff=
       F       F
Bank Sta=160.6,188.92
XS Rating Curve= 0 ,0
Exp/Cntr(USF)=0,0
Exp/Cntr=0.8,0.6

Type RM Length L Ch R = 1 ,632     ,135,127.4,117.4
XS GIS Cut Line= 3
2038449.20440214223701.6853511242038362.23020236223838.836973864
2038257.41514108224038.431611834
#Sta/Elev= 30
       0 1478.72      22 1479.55      26 1479.37    29.8 1478.53    38.5 1474.97
    45.3 1472.75    59.3 1470.77    72.5 1465.93    76.4 1463.32    84.2 1453.58
    87.8 1451.63    91.9 1450.68    95.8  1450.4   103.6 1450.11   111.6 1450.46
   115.2    1450     123 1447.73   134.7 1450.14   138.6 1451.02   147.3 1451.35
   167.8 1454.33   187.8 1455.59   197.9 1455.49   209.9 1456.09   256.3 1456.13
     288 1458.07   321.9 1459.41   346.2 1462.46   375.3 1467.42   387.8 1469.06
#Mann= 6 ,-1 , 0
       0    .016       0      22      .1       0   115.2    .045       0
   134.7      .1       0   197.9    .016       0   209.9     .05       0
#Block Obstruct= 1 ,-1
  172.11  195.99 1475.56
Bank Sta=115.2,134.7
XS Rating Curve= 0 ,0
Exp/Cntr(USF)=0,0
Exp/Cntr=0.3,0.1

Type RM Length L Ch R = 1 ,505     ,128.6,124.8,116.1
XS GIS Cut Line= 3
2038294.21191791223591.2950206262038266.33557182223727.331589522
2038241.80438727224012.785373436
#Sta/Elev= 30
       0 1465.86    34.5  1461.9    47.9 1461.26    71.4 1459.06   108.2 1457.82
   111.6 1457.56     126 1454.83   141.7 1454.12   144.9 1453.28   158.1 1447.95
   164.7 1446.51   171.3 1445.05   174.6 1444.85   177.9 1445.09   182.5 1446.61
   186.8 1447.97     191 1448.61   217.4 1449.89   230.6 1451.11   240.8 1452.67
   276.7 1454.56   283.3 1455.69   288.6 1456.16   309.6 1456.32   316.5 1456.86
   355.7 1459.92   372.2 1462.53   385.7 1463.31   411.7 1466.61   425.4 1467.64
#Mann= 5 ,-1 , 0
       0     .05       0   164.7    .045       0   182.5     .05       0
   288.6    .016       0   316.5     .05       0
#Block Obstruct= 2 ,-1
   54.93  113.27 1480.52  221.38  278.41 1474.86
Bank Sta=164.7,182.5
XS Rating Curve= 0 ,0
Exp/Cntr(USF)=0,0
Exp/Cntr=0.3,0.1

Type RM Length L Ch R = 1 ,380     ,145.8,153.1,159.5
XS GIS Cut Line= 4
2038176.01621051223555.6132976372038138.10437983 223746.28750486
2038152.60007979223843.2971892372038236.22911805224045.121934895
#Sta/Elev= 30
       0  1457.5    54.1 1455.83     101 1455.97   117.7 1454.22   131.1 1451.74
   151.2 1451.79   164.5 1448.91   171.2 1448.32   194.6 1448.29   211.2 1449.01
   214.5  1448.7   223.8 1444.22   234.4 1442.23   237.8 1442.09   241.1 1442.51
   245.2 1444.48     251 1448.44   254.3 1449.85     261  1451.8   270.9 1455.51
   274.3 1456.19   290.8 1457.31   304.9 1457.66   324.2 1459.75   336.4  1460.3
   344.3  1459.4   354.6 1459.43   366.9 1461.92   429.7 1464.39     511  1468.5
#Mann= 5 ,-1 , 0
       0     .05       0   223.8    .045       0   245.2     .05       0
   336.4    .016       0   366.9     .05       0
#XS Ineff= 2 , 0
          209.58 1449.27
Permanent Ineff=
       F       F
#Block Obstruct= 2 ,-1
    9.02   69.45 1477.12  271.72  292.49 1477.36
Bank Sta=223.8,245.2
XS Rating Curve= 0 ,0
Exp/Cntr(USF)=0,0
Exp/Cntr=0.3,0.1

Type RM Length L Ch R = 1 ,227     ,103,77.2,89
XS GIS Cut Line= 4
 2038109.1129799223545.577813046 2038024.3688878223679.384274256
2037986.45705713223799.810089344 2037957.4656572224028.396127244
#Sta/Elev= 30
       0 1456.52      33 1456.52   113.6 1455.51   144.6 1454.47   170.3 1452.61
   177.2 1451.62   187.5 1448.45   190.9 1446.86   196.9 1443.44   197.8 1442.93
   201.2 1442.16   208.1 1441.73   211.6 1441.94   216.6 1443.53   228.8 1448.72
   232.2 1448.94   235.6 1448.39   240.1 1448.46   253.2 1449.52   263.2 1449.04
   266.6 1449.27     270  1450.1   276.9 1453.59   287.1 1454.83   343.3 1456.78
   363.2 1457.14   452.5 1456.67   462.4  1457.1     476 1456.65   515.1 1456.35
#Mann= 3 ,-1 , 0
       0     .05       0   196.9    .045       0   216.6      .1       0
#Block Obstruct= 2 ,-1
       0   45.35 1476.52  405.67  456.04 1476.86
Bank Sta=196.9,216.6
XS Rating Curve= 0 ,0
Exp/Cntr(USF)=0,0
Exp/Cntr=0.3,0.1

Type RM Length L Ch R = 1 ,150     ,,,
XS GIS Cut Line= 4
2038115.58801894223511.1414415532037951.92442327223631.977180414
2037925.92179592223748.224220331 2037944.2765917224020.487024346
#Sta/Elev= 30
       0  1455.5    24.2 1455.42    55.4 1456.08    68.8 1455.35   120.7 1453.97
   149.2 1452.51   153.3 1452.19   157.4 1451.23   165.5 1447.85   179.1 1442.95
   181.9 1442.02   185.9 1441.36     190 1441.22     357 1441.36   366.9 1442.02
   383.3 1444.06   392.5 1444.38   403.1 1445.16   423.3 1447.91   432.6  1450.2
   439.2 1451.01   465.5 1451.84   475.4  1452.8     488  1453.4   497.2 1455.22
     505 1456.15   514.9 1456.43   531.3 1456.36   546.5  1456.8   595.4 1456.48
#Mann= 3 ,-1 , 0
       0     .05       0   185.9    .045       0     357      .1       0
#Block Obstruct= 2 ,-1
    2.17   84.48 1475.55   481.2  537.42  1476.6
Bank Sta=185.9,357
XS Rating Curve= 0 ,0
Exp/Cntr(USF)=0,0
Exp/Cntr=0.3,0.1
LCMann Table=0

Chan Stop Cuts=-1
Use User Specified Reach Order=0
Composite Channel Slope=5